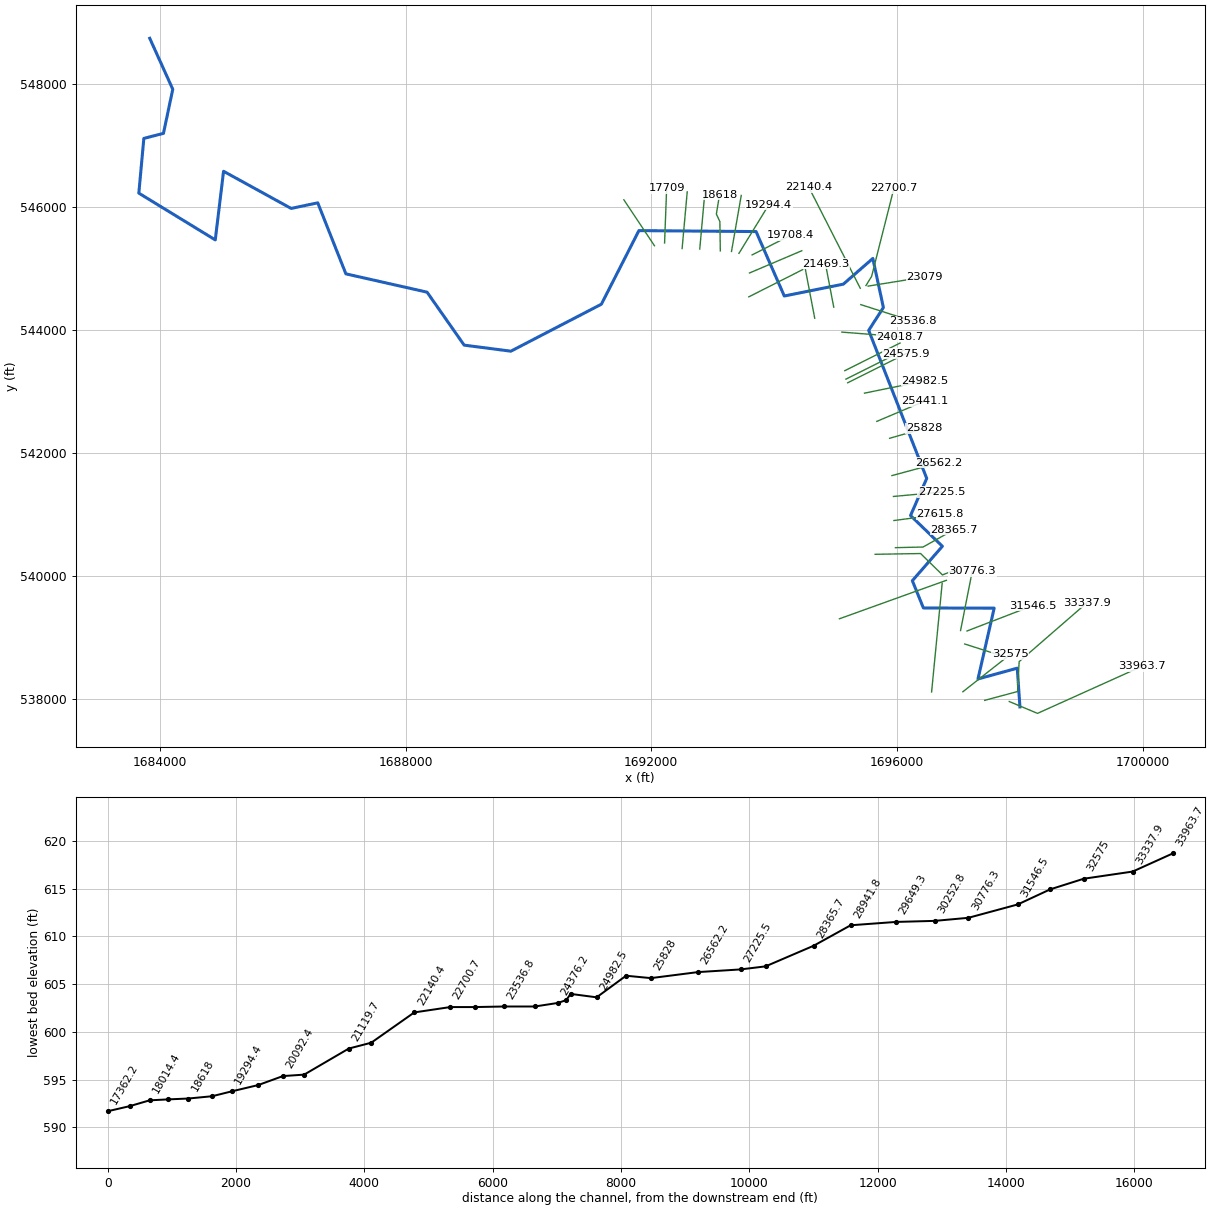
--- PoplarFk.prj (project) ---

Proj Title=PoplarFk
Current Plan=p01
Default Exp/Contr=0,0
English Units
Geom File=g01
Flow File=f01
Plan File=p01
BEGIN DESCRIPTION:
AMEC Environment & Infrastructure, 2013
Projection: NAD 1983 State Plane West Virginia South FIPS 4702 (US Feet)
Vertical Datum: NAVD 1988
END DESCRIPTION:
DSS Export Rating Curves= 0
DSS Export Rating Curve Sorted= 0
DSS Export Volume Flow Curves= 0
DXF OffsetX= 0
DXF OffsetY= 0
DXF ScaleX= 0
DXF ScaleY= 0

--- PoplarFk.p01 (plan) ---

Plan Title=Floodplain
Program Version=4.00
Geom File=g01
Flow File=f01
K Sum by GR=0
Std Step Tol=0.01
Critical Tol=0.01
Num of Std Step Trials=20
Max Error Tol=0.3
Flow Tol Ratio=0.001
Split Flow NTrial=30
Split Flow Tol=0.02
Split Flow Ratio=0.02
Log Output Level=0
Friction Slope Method=1
Unsteady Friction Slope Method=2
Unsteady Bridges Friction Slope Method=1
Global Log Level=0
CheckData=False
Run HTab=0
Run UNet=0
Run PostProcess=0
UNET Theta=0
UNET Theta Warmup=0
UNET ZTol=0
UNET ZSATol=0
UNET MxIter=0
UNET MaxInSteps=0
UNET DtIC=0
UNET DtMin=0
UNET MaxCRTS=0
UNET WFStab=0
UNET SFStab=0
UNET WFX=0
UNET SFX=0
UNET DSS MLevel=0
UNET DZMax Abort=0
UNET Convert EG Bridges=0
UNET Use Existing IB Tables=0
UNET Froude Limit=0
UNET Froude Power=0
Write IC File=0
Echo Input=False
Echo Output=False
Write Detailed=0

--- PoplarFk.f01 (steady flow) ---

Flow Title=USGS Regress. Eqn. (2010) - Western-Plateaus
Program Version=4.10
Number of Profiles= 1
Profile Names=P100yr
River Rch & RM=PoplarFk,Main            ,33963.7
    2691
River Rch & RM=PoplarFk,Main            ,32575
    3167
River Rch & RM=PoplarFk,Main            ,29649.3
    3351
River Rch & RM=PoplarFk,Main            ,25441.1
    3440
River Rch & RM=PoplarFk,Main            ,24575.9
    3484
River Rch & RM=PoplarFk,Main            ,22140.4
    3542
River Rch & RM=PoplarFk,Main            ,17362.2
    3846
River Rch & RM=PoplarFk,Main            ,15091
    3872
River Rch & RM=PoplarFk,Main            ,11194.7
    3924
River Rch & RM=PoplarFk,Main            ,7539.5
    4767
River Rch & RM=PoplarFk,Main            ,4890.1
    4805
River Rch & RM=PoplarFk,Main            ,2565.2
    4873
River Rch & RM=PoplarFk,Main            ,19.7
    4907
Boundary for River Rch & Prof#=PoplarFk,Main            , 1
Up Type= 0
Dn Type= 3
Dn Slope=0.000998
DSS Import GetInterval= 0
DSS Import GetPeak= 0
DSS Import FillOption= 0

--- PoplarFk.g01 (geometry) ---

Geom Title=USGS 3m DEM
Program Version=4.10

River Reach=PoplarFk        ,Main
Reach XY= 30
      1698003.32       537870.82     1697959.804       538501.22
     1697320.057      538325.321     1697583.767      539477.509
     1696431.595      539480.465     1696251.429      539924.328
     1696740.795      540484.087     1696222.284      540984.337
     1696485.804       541588.39     1695540.915      543996.713
     1695780.075      544368.338       1695608.2      545166.515
     1695127.732      544748.546     1694166.794      544555.838
     1693707.159      545604.015     1691799.607       545619.64
      1691188.88      544422.303     1689715.373      543658.128
     1688954.554      543756.359     1688350.388      544618.338
     1687028.914      544916.221     1686570.995      546071.385
     1686137.532      545980.321     1685037.311      546584.962
     1684902.471      545468.598     1683657.655      546229.301
     1683739.639      547119.719     1684058.722      547201.795
     1684210.616      547918.999     1683835.803      548747.705

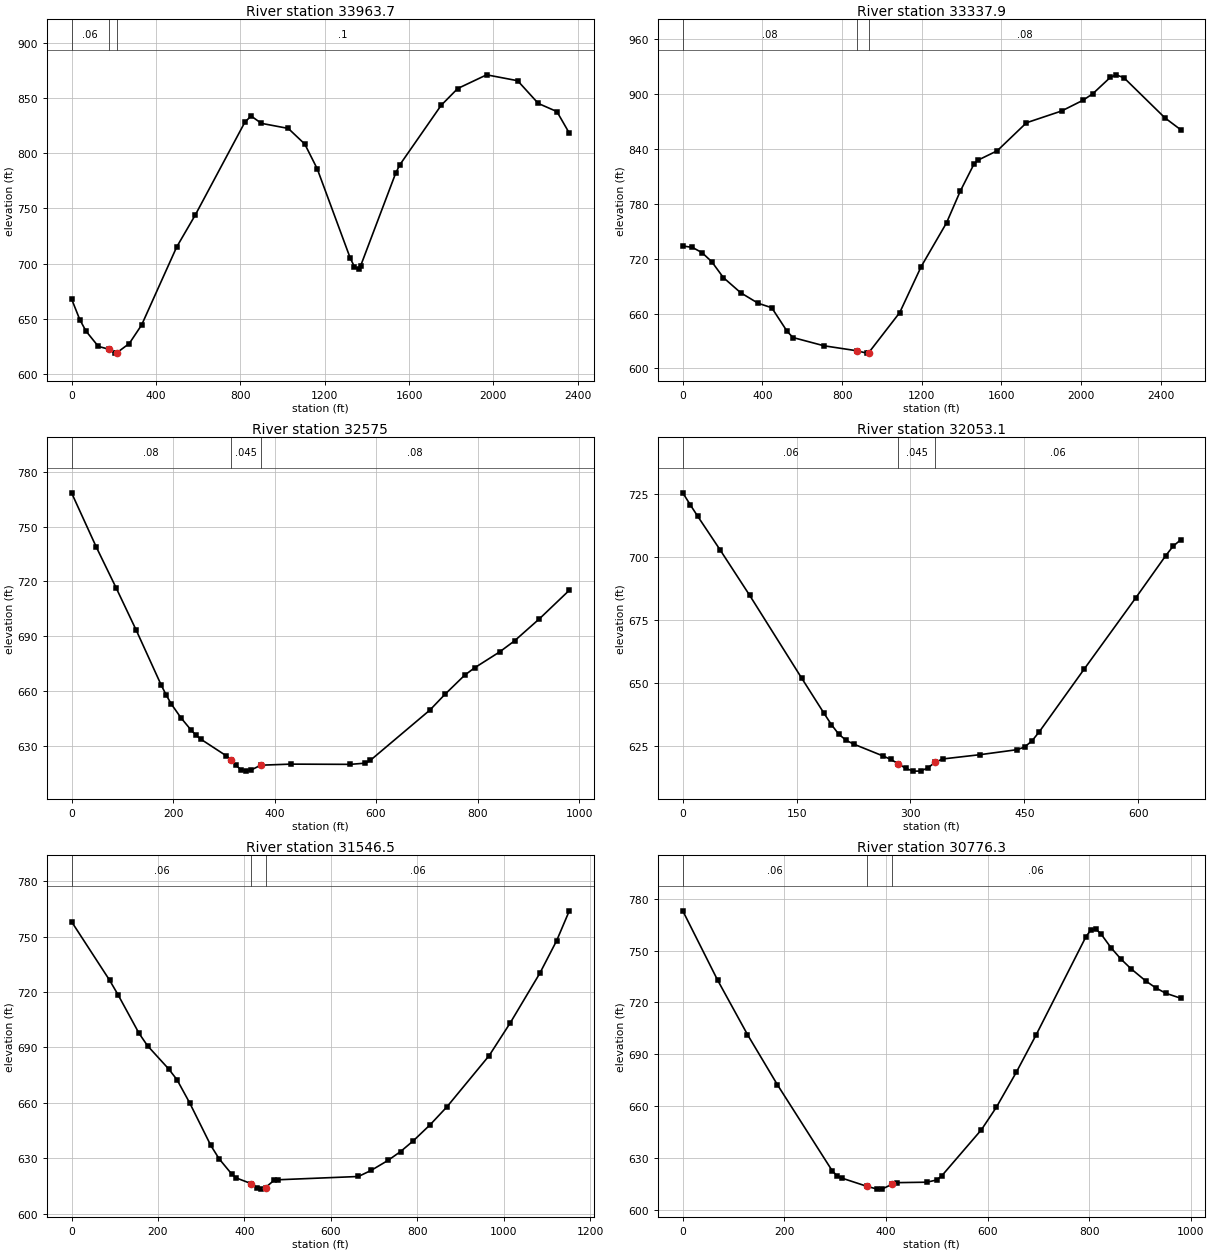
Type RM Length L Ch R = 1 ,33963.7 ,546,625.8,674.8
XS GIS Cut Line= 3
     1697829.795      537958.414     1698289.273      537765.695
     1699986.705      538529.891
#Sta/Elev= 30
       0   667.9    39.1  649.08    68.4  638.69     127  624.78   175.9  622.29
   205.2  618.68   214.5 618.987   273.6   627.4   332.2  644.23   498.3  714.99
   586.4  744.01   821.6  828.29     851  833.96     900  827.27  1027.3  822.67
  1105.7  808.46  1164.5  786.12  1321.2  704.93  1340.8  697.16  1360.4  694.64
  1370.2  697.72  1536.8  782.11  1556.4  789.67  1752.3  843.65  1830.7  858.88
  1967.9  871.32  2114.8  865.98  2212.8  845.34    2301  837.96  2359.8  818.38
#Mann= 3 , 0 , 0
       0     .06       0   175.9    .045       0   214.5      .1       0
Bank Sta=175.9,214.5
XS Rating Curve= 0 ,0
Exp/Cntr=0.3,0.1

Type RM Length L Ch R = 1 ,33337.9 ,816.8,762.9,737.3
XS GIS Cut Line= 4
      1697429.61      537977.737     1697964.181      538120.866
     1697990.197      538607.102      1699092.31      539563.082
#Sta/Elev= 30
       0  733.96    48.5  732.39    97.1  726.59   145.6  716.74   203.9  699.37
   291.3  682.74   378.6  671.28   446.6  666.45   524.3  640.49   553.4  633.83
   709.2   624.8   874.5 619.354   923.5  616.78   932.7 616.989  1089.3  661.12
    1197  711.39  1324.3  759.22  1392.8  793.66  1461.4   823.2    1481  827.68
  1578.9  838.07  1725.8  868.72    1902  881.57  2009.7  893.33  2058.7  900.44
  2146.8  918.37  2176.2  921.13  2215.3  917.91    2421  874.06  2499.3  861.24
#Mann= 3 , 0 , 0
       0     .08       0   874.5    .045       0   932.7     .08       0
Bank Sta=874.5,932.7
XS Rating Curve= 0 ,0
Exp/Cntr=0.3,0.1

Type RM Length L Ch R = 1 ,32575   ,544.5,521.9,499.3
XS GIS Cut Line= 2
     1697074.633      538117.701     1697845.373      538724.268
#Sta/Elev= 30
       0   768.6      49  738.72    88.3  716.23   127.5  693.25   176.5   663.3
   186.4  657.82   196.2  652.96   215.8  645.17   235.4  638.59   245.2  635.72
     255  633.49     304  624.59   314.2  622.32   323.7  619.26   333.5  616.87
   343.3  616.03   353.1  616.53   372.7  619.28   431.6  619.87   549.2  619.74
   578.7   620.4   588.5  621.89   706.2  649.53   735.6  658.08   774.8  668.67
   794.4  672.71   843.5  681.38   872.9  687.46     922  699.56   980.8  715.18
#Mann= 3 , 0 , 0
       0     .08       0   314.2    .045       0   372.7     .08       0
Bank Sta=314.2,372.7
XS Rating Curve= 0 ,0
Exp/Cntr=0.3,0.1

Type RM Length L Ch R = 1 ,32053.1 ,491.7,506.5,520.6
XS GIS Cut Line= 2
     1697104.576      538894.361     1697729.484      538695.115
#Sta/Elev= 30
       0  725.61     9.8  720.88    19.6  716.32      49  703.01    88.1  684.86
   156.6  651.94     186  637.98   195.8  633.44   205.6  629.59   215.4  627.16
   225.2  625.67   264.3   620.9   274.1  619.57   283.9  617.87   293.7  616.03
   303.5  614.92   313.3  614.93   323.1  616.24   332.8  618.49   342.6  619.76
   391.6  621.46   440.5  623.45   450.3  624.48   460.1  626.92   469.9  630.62
   528.6  655.36   597.2  683.96   636.3  700.58   646.1  704.37   655.9  706.86
#Mann= 3 , 0 , 0
       0     .06       0   283.9    .045       0   332.8     .06       0
Bank Sta=283.9,332.8
XS Rating Curve= 0 ,0
Exp/Cntr=0.3,0.1

Type RM Length L Ch R = 1 ,31546.5 ,746.3,770.2,794.3
XS GIS Cut Line= 2
     1697141.412      539105.999     1698216.437      539520.388
#Sta/Elev= 30
       0   758.1    87.9  726.46   107.4  718.62   156.2  697.66   175.8  690.94
   224.6  678.43   244.1  672.54   273.4  660.01   322.2  637.02   341.7  629.71
     371  621.41   380.8  619.43   415.8 616.308   429.6  614.01   439.4  613.34
   449.1  614.22   468.7  618.12   478.4  618.41   663.9  620.18   693.2  623.45
   732.3  628.86   761.6  633.68   790.9  639.47   829.9  648.16     869  657.92
   966.6   685.6  1015.4  703.31  1083.8  730.15  1122.8   747.8  1152.1  763.96
#Mann= 3 , 0 , 0
       0     .06       0   415.8    .045       0   449.1     .06       0
Bank Sta=415.8,449.1
XS Rating Curve= 0 ,0
Exp/Cntr=0.3,0.1

Type RM Length L Ch R = 1 ,30776.3 ,521.8,523.5,525
XS GIS Cut Line= 2
     1697036.781       539113.37     1697226.016      540074.439
#Sta/Elev= 30
       0  773.04    68.6  732.89   127.3  701.43   186.1  672.42   293.9  622.64
   303.6  619.63   313.4  618.28   362.6 613.541     382     612   391.8  611.94
   411.2 614.665   421.2  615.69     480  615.95   499.6  617.22   509.4  619.56
   587.7  646.33   617.1  659.34   656.3  679.57   695.5  701.32   793.4  758.06
   803.2  762.03     813  762.38   822.8  759.74   842.4   751.8     862  745.18
   881.6  739.63     911  732.46   930.6  728.49   950.1  725.37   979.5  722.49
#Mann= 3 , 0 , 0
       0     .06       0   362.6    .045       0   411.2     .06       0
Bank Sta=362.6,411.2
XS Rating Curve= 0 ,0
Exp/Cntr=0.3,0.1

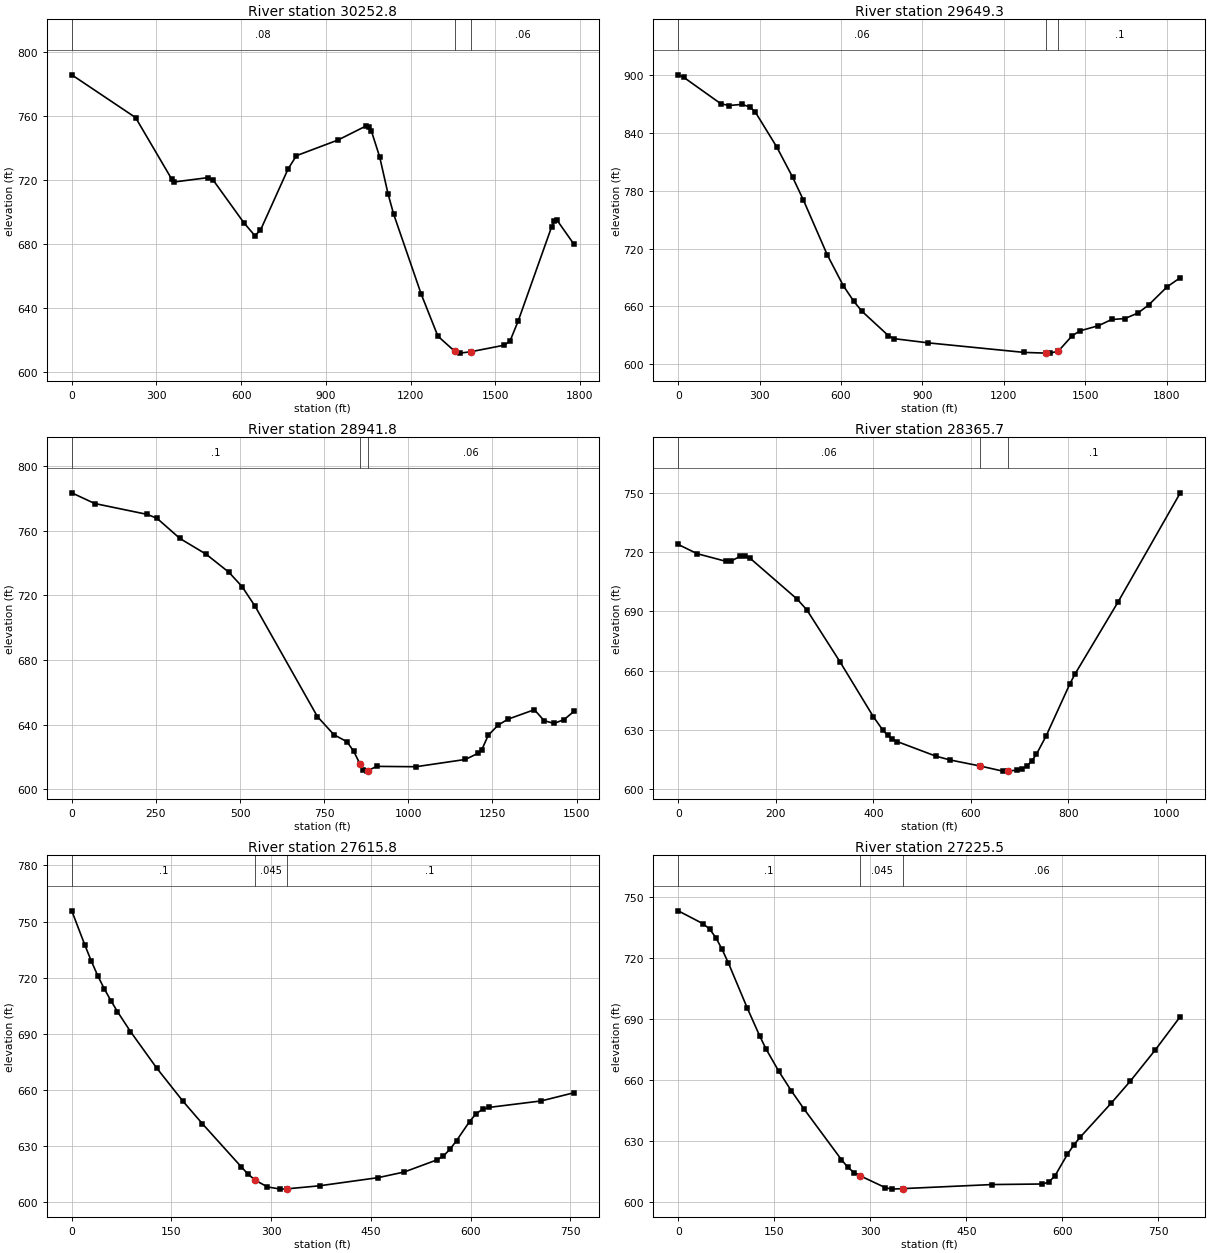
Type RM Length L Ch R = 1 ,30252.8 ,630.6,603.5,575.8
XS GIS Cut Line= 2
     1696565.155       538114.43      1696737.45      539884.325
#Sta/Elev= 30
       0  785.83     226  759.07   353.7  720.63   363.5  718.77   481.4  721.45
   501.1  719.87   609.1  693.34   648.4  685.15   668.1  688.46   766.3  726.97
   795.8  735.22   943.2  745.04  1041.4  753.74  1051.2   753.4  1061.1  750.71
  1090.5   734.5    1120  711.48  1139.7  698.81  1237.9  648.44  1296.8  622.23
    1356  612.84  1375.4  611.62  1414.8  612.53  1532.6  616.62  1552.3  619.21
  1581.8  632.04  1699.7  690.73  1709.5  694.32  1719.3  694.69  1778.3  679.88
#Mann= 3 , 0 , 0
       0     .08       0    1356    .045       0  1414.8     .06       0
Bank Sta=1356,1414.8
XS Rating Curve= 0 ,0
Exp/Cntr=0.3,0.1

Type RM Length L Ch R = 1 ,29649.3 ,733.2,707.5,681.7
XS GIS Cut Line= 3
     1695064.647      539304.742     1696412.421      539789.438
     1696806.483      539930.331
#Sta/Elev= 30
       0   900.3    19.6  897.84     157   870.3   186.4  868.46   235.4  869.63
   264.9   866.8   284.5   861.5     363  825.51   421.8     794   461.1  770.55
   549.4  713.47   608.2  681.61   647.5  665.14   676.9  655.04     775  629.55
   794.6  626.56   922.2  622.14  1275.3  612.24  1354.8 611.529  1369.4  611.51
  1400.7 613.449  1451.7  629.43  1480.9  634.63  1549.1  639.98  1597.7  646.41
  1646.4  647.37    1695  653.16    1734  661.47  1802.1  680.31  1850.8  689.82
#Mann= 3 , 0 , 0
       0     .06       0  1354.8    .045       0  1400.7      .1       0
Bank Sta=1354.8,1400.7
XS Rating Curve= 0 ,0
Exp/Cntr=0.3,0.1

Type RM Length L Ch R = 1 ,28941.8 ,547.1,576.1,552.4
XS GIS Cut Line= 4
      1695645.87      540353.722     1696385.581       540366.23
     1696741.898      540018.445     1696979.032      540110.455
#Sta/Elev= 30
       0  783.31    68.1   776.7   223.9  769.98   253.1  767.59   321.2   755.1
   399.1  745.37   467.2  734.14   506.2  725.28   545.1  713.05   730.1  644.87
   778.9  633.72   817.9  629.32   837.4  623.59     857  615.45   866.7  612.01
   876.5  611.16     881 611.532   905.8   614.1  1022.9  613.88  1169.4  618.37
  1208.4  622.28  1218.2  624.25  1237.7  633.32  1267.1  639.63  1296.4  643.29
  1374.7  649.15    1404  642.34  1433.4   640.7  1462.7  642.99  1492.1  648.06
#Mann= 3 , 0 , 0
       0      .1       0     857    .045       0     881     .06       0
Bank Sta=857,881
XS Rating Curve= 0 ,0
Exp/Cntr=0.3,0.1

Type RM Length L Ch R = 1 ,28365.7 ,751.2,749.9,695
XS GIS Cut Line= 3
     1695975.905      540461.692     1696424.806      540471.699
     1696931.691      540754.269
#Sta/Elev= 30
       0  723.87      39  719.18    97.6  715.35   107.4  715.34   126.9  717.86
   136.7  718.16   146.4  717.08     244  696.12   263.6  690.75   331.9   664.3
   400.2  636.52   419.7  629.72   429.5   627.1   439.2  625.17     449  623.99
   527.7  616.65   557.2  614.68   618.9  611.61   665.4  609.02   675.4 609.033
   694.9  609.53   704.8  610.22   714.6  611.56   724.4  614.03   734.3  617.57
   753.9  626.68   803.1  653.36     813  658.04   901.5  694.66  1029.3  750.04
#Mann= 3 , 0 , 0
       0     .06       0   618.9    .045       0   675.4      .1       0
Bank Sta=618.9,675.4
XS Rating Curve= 0 ,0
Exp/Cntr=0.3,0.1

Type RM Length L Ch R = 1 ,27615.8 ,390.9,390.2,389.8
XS GIS Cut Line= 2
     1695951.952      540903.074     1696700.752      541002.221
#Sta/Elev= 30
       0  755.74    19.6  737.52    29.4  728.85    39.2  720.93      49  713.96
    58.9  707.68    68.7  701.84    88.3  691.16   127.5  671.76   166.8  654.09
   196.2  641.96     255  618.78   264.9  614.96   276.3  611.56   294.3  608.06
   313.9  606.86   323.1 606.992   372.8  608.65     461  613.01   500.3  616.04
   549.3   622.5   559.1  624.61     569  628.21   578.8   632.8   598.4  642.99
   608.2  647.18     618  649.58   627.8  650.58   706.3  654.05   755.3  658.41
#Mann= 3 , 0 , 0
       0      .1       0   276.3    .045       0   323.1      .1       0
Bank Sta=276.3,323.1
XS Rating Curve= 0 ,0
Exp/Cntr=0.3,0.1

Type RM Length L Ch R = 1 ,27225.5 ,657.2,663.4,666
XS GIS Cut Line= 2
     1695944.153      541294.573     1696725.044      541366.985
#Sta/Elev= 30
       0  743.32    39.2   736.9      49  734.35    58.8  730.12    68.6  724.32
    78.4  717.62   107.8  695.56   127.4  681.71   137.2  675.39   156.8  664.59
   176.4  654.98   196.1  646.07   254.9  621.03   264.7  617.33   274.5   614.7
   284.2 613.077   323.5  607.27   333.3  606.54   350.7 606.788   490.2  608.79
   568.6  609.06   578.4  609.94   588.2  612.96   607.8  623.61   617.6  628.14
   627.4  631.92   676.4  648.84   705.8  659.51     745  674.91   784.2  691.36
#Mann= 3 , 0 , 0
       0      .1       0   284.2    .045       0   350.7     .06       0
Bank Sta=284.2,350.7
XS Rating Curve= 0 ,0
Exp/Cntr=0.3,0.1

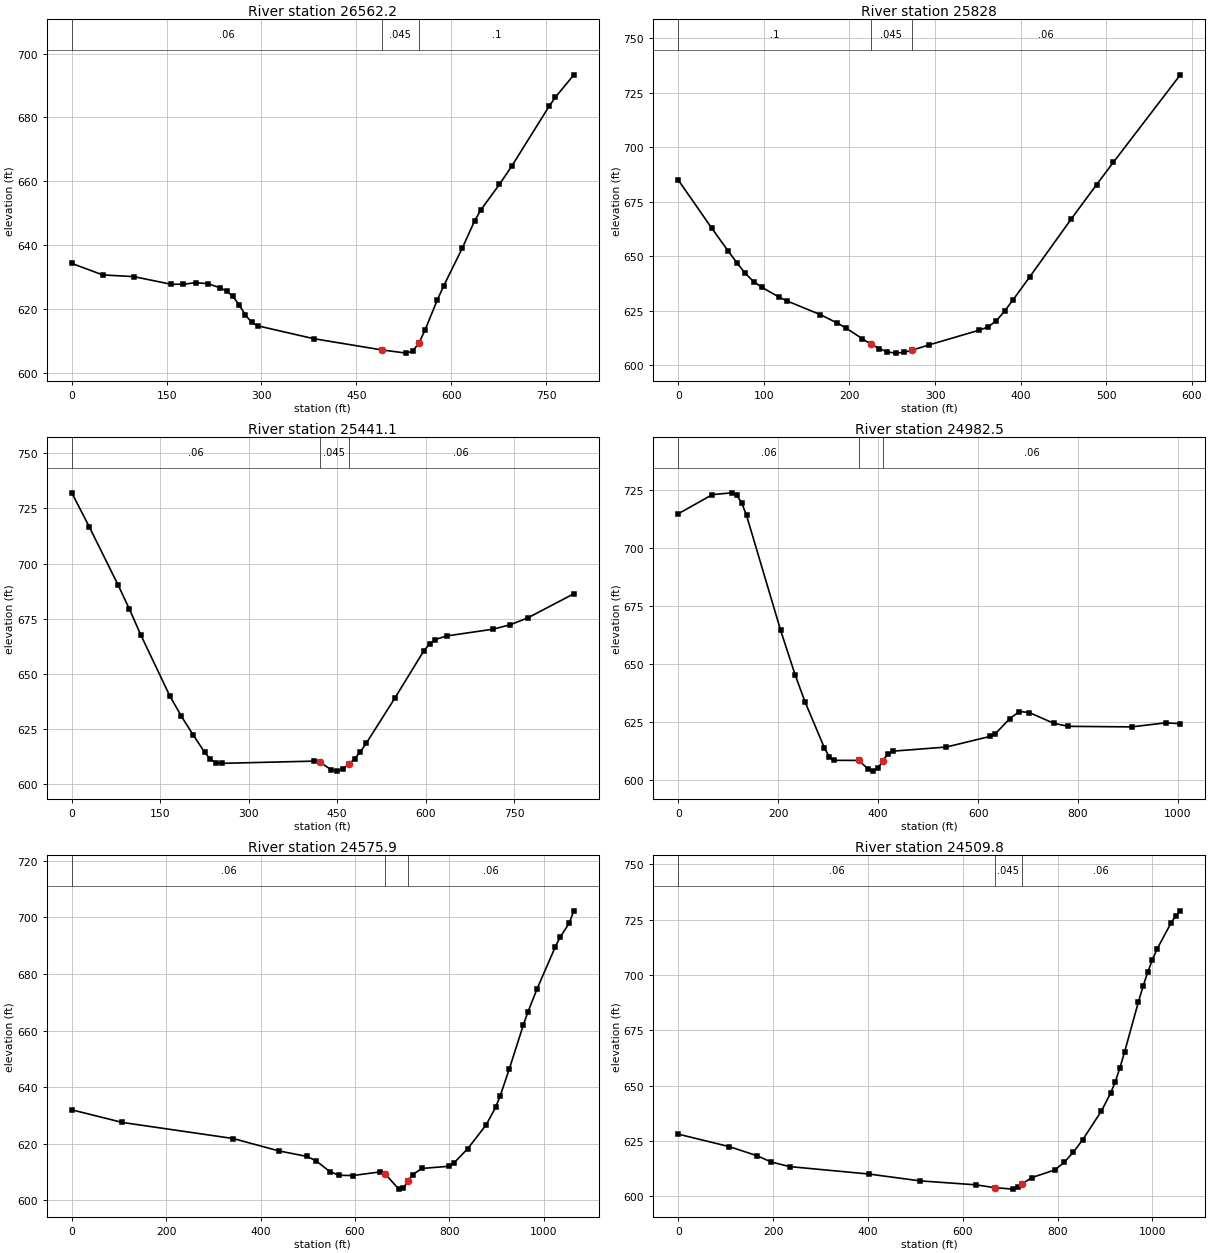
Type RM Length L Ch R = 1 ,26562.2 ,730.6,734.1,736.9
XS GIS Cut Line= 2
     1695919.953      541634.238     1696686.522      541840.972
#Sta/Elev= 30
       0  634.33      49  630.73      98   630.2   156.8  627.82   176.4   627.8
     196  628.31   215.6  627.99   235.2  626.65     245  625.64   254.8  624.03
   264.6   621.4   274.4  618.26   284.3  615.92   294.1   614.8   382.3  610.79
   490.1  607.27     529  606.26   539.1  606.91   548.9  609.34   558.7  613.52
   578.3  622.99   588.1  627.26   617.5  639.09   637.1  647.68   646.9  651.06
   676.3  659.05   695.9   664.8   754.8  683.46   764.6  686.28     794  693.34
#Mann= 3 , 0 , 0
       0     .06       0   490.1    .045       0   548.9      .1       0
Bank Sta=490.1,548.9
XS Rating Curve= 0 ,0
Exp/Cntr=0.3,0.1

Type RM Length L Ch R = 1 ,25828   ,385.5,386.9,388.4
XS GIS Cut Line= 2
     1695881.366      542240.921     1696445.076      542402.359
#Sta/Elev= 30
       0  685.02    39.1  662.94    58.6  652.29    68.4   647.1    78.2  642.23
      88  638.43    97.7  635.79   117.3  631.42     127  629.55   166.1  623.27
   185.7  619.42   195.5  617.26     215  612.22   224.8  609.83   234.6  607.71
   244.3  606.18   254.1  605.63   263.9  606.01   273.2 606.988   293.2  609.44
   351.8  616.18   361.6   617.6   371.4  620.42   381.1  624.86   390.9  629.99
   410.5  640.58   459.3  667.28   488.6  682.89   508.2  693.11   586.4  733.23
#Mann= 3 , 0 , 0
       0      .1       0   224.8    .045       0   273.2     .06       0
Bank Sta=224.8,273.2
XS Rating Curve= 0 ,0
Exp/Cntr=0.3,0.1

Type RM Length L Ch R = 1 ,25441.1 ,462.4,458.6,454.5
XS GIS Cut Line= 2
     1695673.453      542516.209     1696457.278      542847.965
#Sta/Elev= 30
       0  732.05    29.4  716.78    78.3  690.39    97.8  679.28   117.4  667.41
   166.3  639.93   185.9  630.72   205.4  622.46     225  614.52   234.8  611.26
   244.6  609.64   254.4  609.41   410.9  610.42   420.7  609.94   440.2  606.41
     450  605.88   459.8  606.92   469.4 608.918   479.4  611.49   489.2  614.64
     499  618.43   547.9  639.09   596.8  660.42   606.6  663.55   616.3  665.55
   635.9  667.18   714.2  670.23   743.5  672.27   772.9  675.34   851.1  686.29
#Mann= 3 , 0 , 0
       0     .06       0   420.7    .045       0   469.4     .06       0
Bank Sta=420.7,469.4
XS Rating Curve= 0 ,0
Exp/Cntr=0.3,0.1

Type RM Length L Ch R = 1 ,24982.5 ,400.7,406.7,412.4
XS GIS Cut Line= 2
     1695472.776      542975.288     1696457.048      543176.539
#Sta/Elev= 30
       0  714.55    68.3  722.83   107.3  723.59     117   722.6   126.8  719.32
   136.6   713.9   204.8  664.36   234.1  644.99   253.6  633.54   292.6  613.56
   302.4  609.74   312.1  608.27   360.9  608.24   380.4  604.46   390.2  603.62
   399.9  604.96   409.4 608.091   419.4  611.04   429.2  612.22   536.5  614.01
   624.2   618.6     634  619.61   663.2  626.22   682.8  629.32   702.3  628.88
     751  624.27   780.3  622.93   907.1  622.69   975.4  624.44  1004.6  624.06
#Mann= 3 , 0 , 0
       0     .06       0   360.9    .045       0   409.4     .06       0
Bank Sta=360.9,409.4
XS Rating Curve= 0 ,0
Exp/Cntr=0.3,0.1

Type RM Length L Ch R = 1 ,24575.9 ,66.4,66.1,65.9
XS GIS Cut Line= 2
     1695198.637      543143.962     1696149.937       543619.36
#Sta/Elev= 30
       0  631.99   107.3  627.53   341.5  621.86     439  617.47   497.6  615.54
   517.1  614.03   546.4   610.2   565.9  608.87   595.2  608.77   653.7  610.08
   663.4  609.44   692.7  603.98   702.5  604.34     712 606.798     722  609.09
   741.5  611.27     800  612.07   809.8  613.27   839.1  618.33   878.1  626.76
   897.6  632.82   907.4  636.88   926.9  646.48   956.2  661.81   965.9  666.42
   985.4  674.62  1024.4  689.62  1034.2  692.88  1053.7  697.93  1063.5  702.28
#Mann= 3 , 0 , 0
       0     .06       0   663.4    .045       0     712     .06       0
Bank Sta=663.4,712
XS Rating Curve= 0 ,0
Exp/Cntr=0.3,0.1

Type RM Length L Ch R = 1 ,24509.8 ,133.5,133.6,133.5
XS GIS Cut Line= 2
     1695169.831      543202.939     1696116.966      543676.256
#Sta/Elev= 30
       0  628.17   107.8  622.52   166.7  618.38   196.1  615.56   235.3   613.5
     402  610.15   509.8  607.06   627.4  605.28     667 604.018   705.9  603.33
   715.7  604.07   725.3 605.677   745.1  608.49   794.1     612   813.7  615.38
   833.3  620.05   852.9  625.63   892.2  638.52   911.8  646.68   921.6  651.77
   931.4  658.08   941.2  665.23   970.6  688.04   980.4  695.04   990.2   701.4
    1000  706.95  1009.8  711.81  1039.2  723.53    1049  726.76  1058.8  729.04
#Mann= 3 , 0 , 0
       0     .06       0     667    .045       0   725.3     .06       0
Bank Sta=667,725.3
XS Rating Curve= 0 ,0
Exp/Cntr=0.3,0.1

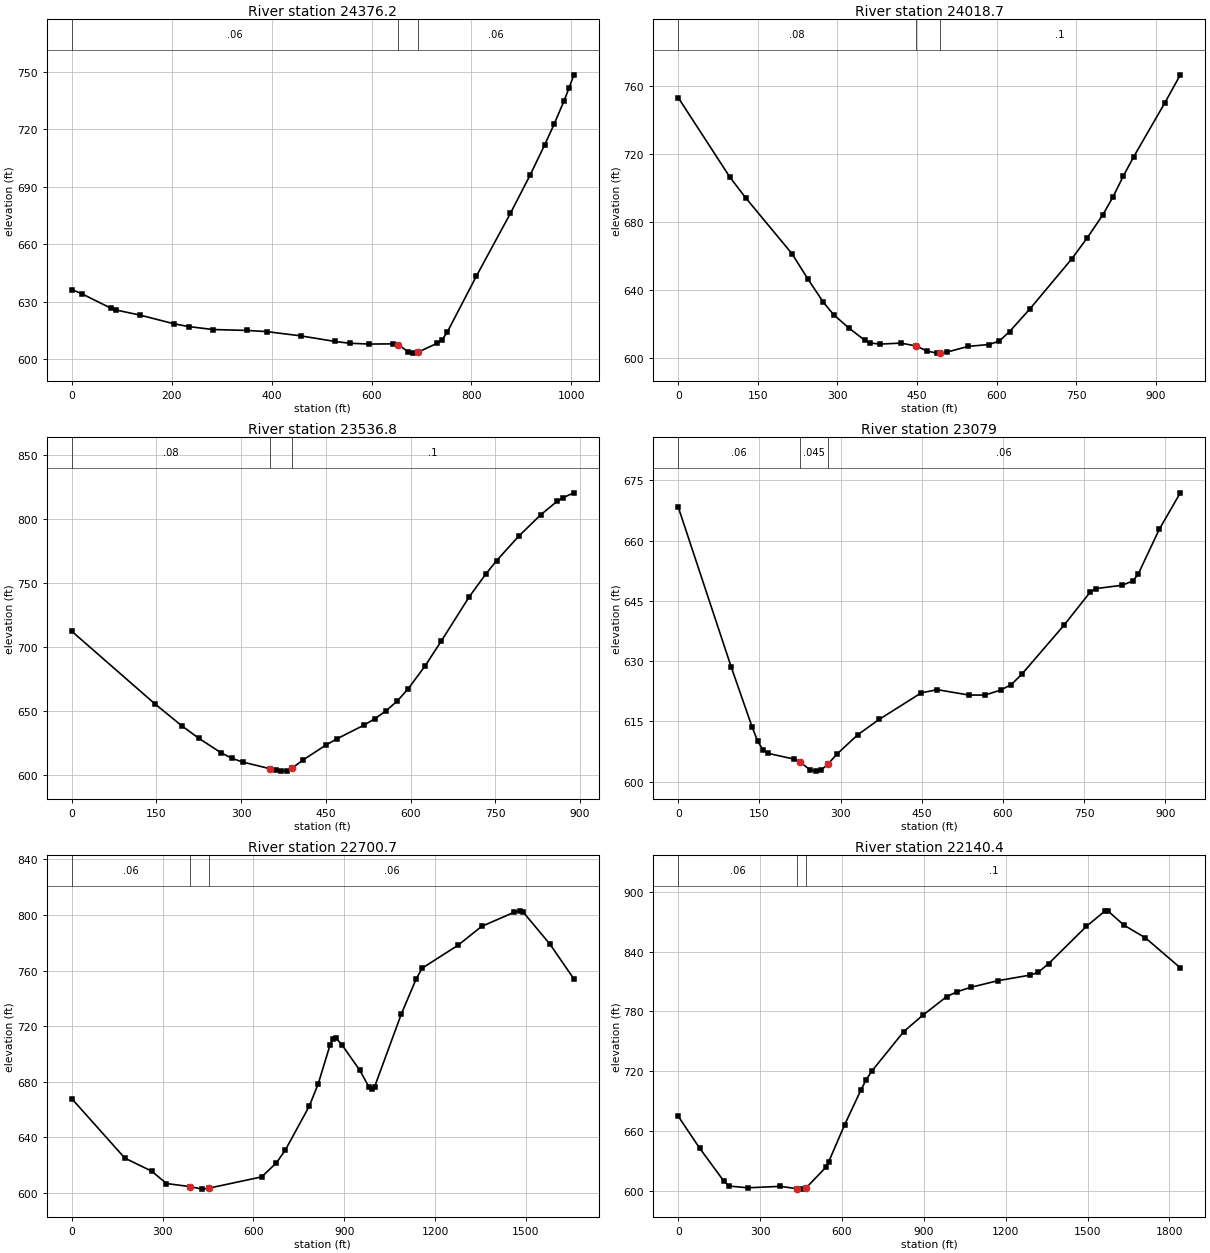
Type RM Length L Ch R = 1 ,24376.2 ,374,357.5,336.6
XS GIS Cut Line= 2
     1695152.825      543341.186      1696051.73        543790.4
#Sta/Elev= 30
       0  636.26    19.5  634.15      78  626.56    87.8  625.63   136.6  622.92
   204.9  618.35   234.2   616.9   282.9  615.37   351.2   614.9   390.2  614.28
   458.6  612.05   526.8  609.13   556.1   608.2   595.1  607.77   643.9  607.88
   653.7   607.4   673.2  603.76   682.9  603.03     692 603.392   731.7  608.23
   741.5  610.12   751.2  613.83   809.8  643.29   878.1   676.2   917.1     696
   946.4  711.87   965.9  723.04   985.4  735.04   995.1  741.54  1004.9  748.57
#Mann= 3 , 0 , 0
       0     .06       0   653.7    .045       0     692     .06       0
Bank Sta=653.7,692
XS Rating Curve= 0 ,0
Exp/Cntr=0.3,0.1

Type RM Length L Ch R = 1 ,24018.7 ,483.8,481.9,483.8
XS GIS Cut Line= 2
     1695103.732      543968.376     1696047.184      543894.548
#Sta/Elev= 30
       0  753.17    97.6  706.22   126.8  694.27   214.6  661.14   243.9  646.56
   273.2  632.77   292.7  625.35     322  617.36   351.2  610.31     361  608.66
   380.5  607.98   419.5  608.56   448.8  606.86   468.3  603.95   487.8  602.66
     493 602.724   507.3  603.33   546.3  606.62   585.4  607.73   604.9  609.69
   624.4  615.33   663.4  628.92   741.5  658.12   770.7  670.49     800  684.01
   819.5  694.73     839  707.04   858.5  718.39   917.1  750.08   946.3  766.62
#Mann= 3 , 0 , 0
       0     .08       0   448.8    .045       0     493      .1       0
Bank Sta=448.8,493
XS Rating Curve= 0 ,0
Exp/Cntr=0.3,0.1

Type RM Length L Ch R = 1 ,23536.8 ,446.7,457.8,467.8
XS GIS Cut Line= 2
     1695412.472      544415.319     1696259.667      544145.116
#Sta/Elev= 30
       0  712.01   146.6  655.48   195.4   637.9   224.8  628.42   263.8  617.17
   283.4  612.72   302.9  609.74   351.8  604.45   361.6  603.16   371.3  602.66
   381.1  603.14   390.9  605.28   410.4   611.6   449.5  622.86     469  627.78
   517.9   638.7   537.4  643.79     557  649.99   576.5  657.47   596.1  667.22
   625.4  684.69   654.7  704.53   703.6  738.75   732.9  756.54   752.4  767.25
   791.5   786.3   830.6  803.11   859.9  813.73   869.7  816.38   889.2  820.25
#Mann= 3 , 0 , 0
       0     .08       0   351.8    .045       0   390.9      .1       0
Bank Sta=351.8,390.9
XS Rating Curve= 0 ,0
Exp/Cntr=0.3,0.1

Type RM Length L Ch R = 1 ,23079   ,324.1,378.3,411.8
XS GIS Cut Line= 2
     1695531.627      544716.584     1696447.472       544864.59
#Sta/Elev= 30
       0  668.38    97.7  628.61   136.7  613.51   146.5  610.16   156.2  607.96
     166  607.03   214.8  605.57   224.6  604.92   244.1  602.86   253.9   602.6
   263.7  602.83     276 604.251     293  606.82     332  611.69   371.1  615.47
   449.2   622.1   478.5  622.89   537.1  621.55   566.4  621.54   595.7  622.78
   615.2  624.14   634.8  626.73   712.9  638.96   761.7  647.28   771.5  648.06
   820.3   648.9   839.8  649.96   849.6  651.61   888.7   662.8   927.7  671.92
#Mann= 3 , 0 , 0
       0     .06       0   224.6    .045       0     276     .06       0
Bank Sta=224.6,276
XS Rating Curve= 0 ,0
Exp/Cntr=0.3,0.1

Type RM Length L Ch R = 1 ,22700.7 ,569.3,560.3,570.1
XS GIS Cut Line= 3
      1695496.95      544725.992     1695588.616      544875.325
     1695952.939       546312.69
#Sta/Elev= 30
       0  667.74   175.2  624.94   263.6  615.57   312.7  606.64   391.3  604.38
   430.5   602.6     453 603.311   626.9   611.4     676  621.56   705.5  630.84
   784.1  662.27   813.5  678.17   852.8  706.32   862.6  710.86   872.4  711.39
   892.1  706.56     951  688.21   980.5   676.5   990.3  674.64  1000.1  676.36
  1088.5  728.86  1137.6  754.08  1157.2  761.74  1275.1  778.17  1353.6  791.82
  1461.6  802.04  1481.3  803.02  1491.1  801.98  1579.5  778.91    1658     754
#Mann= 3 , 0 , 0
       0     .06       0   391.3    .045       0     453     .06       0
Bank Sta=391.3,453
XS Rating Curve= 0 ,0
Exp/Cntr=0.3,0.1

Type RM Length L Ch R = 1 ,22140.4 ,679.2,671.1,661.2
XS GIS Cut Line= 2
     1695403.775      544681.648     1694568.252      546321.083
#Sta/Elev= 30
       0  675.06    78.7     643   167.3  609.99     187  605.11   255.8  603.38
   373.9  604.82     434 602.517   452.6  602.04     469 603.405   541.2  623.97
     551  629.15   610.1  666.65   669.1  701.09   688.8  711.62   708.5  719.94
   826.6  759.89   895.4  776.03     984  794.91  1023.4  799.92  1072.6  804.22
    1171   810.8    1289  816.41  1318.6  819.08  1357.9  828.03  1495.7   865.2
  1564.6  880.82  1574.4   880.8  1633.4  866.49  1712.2  853.72  1840.1  823.73
#Mann= 3 , 0 , 0
       0     .06       0     434    .045       0     469      .1       0
Bank Sta=434,469
XS Rating Curve= 0 ,0
Exp/Cntr=0.3,0.1

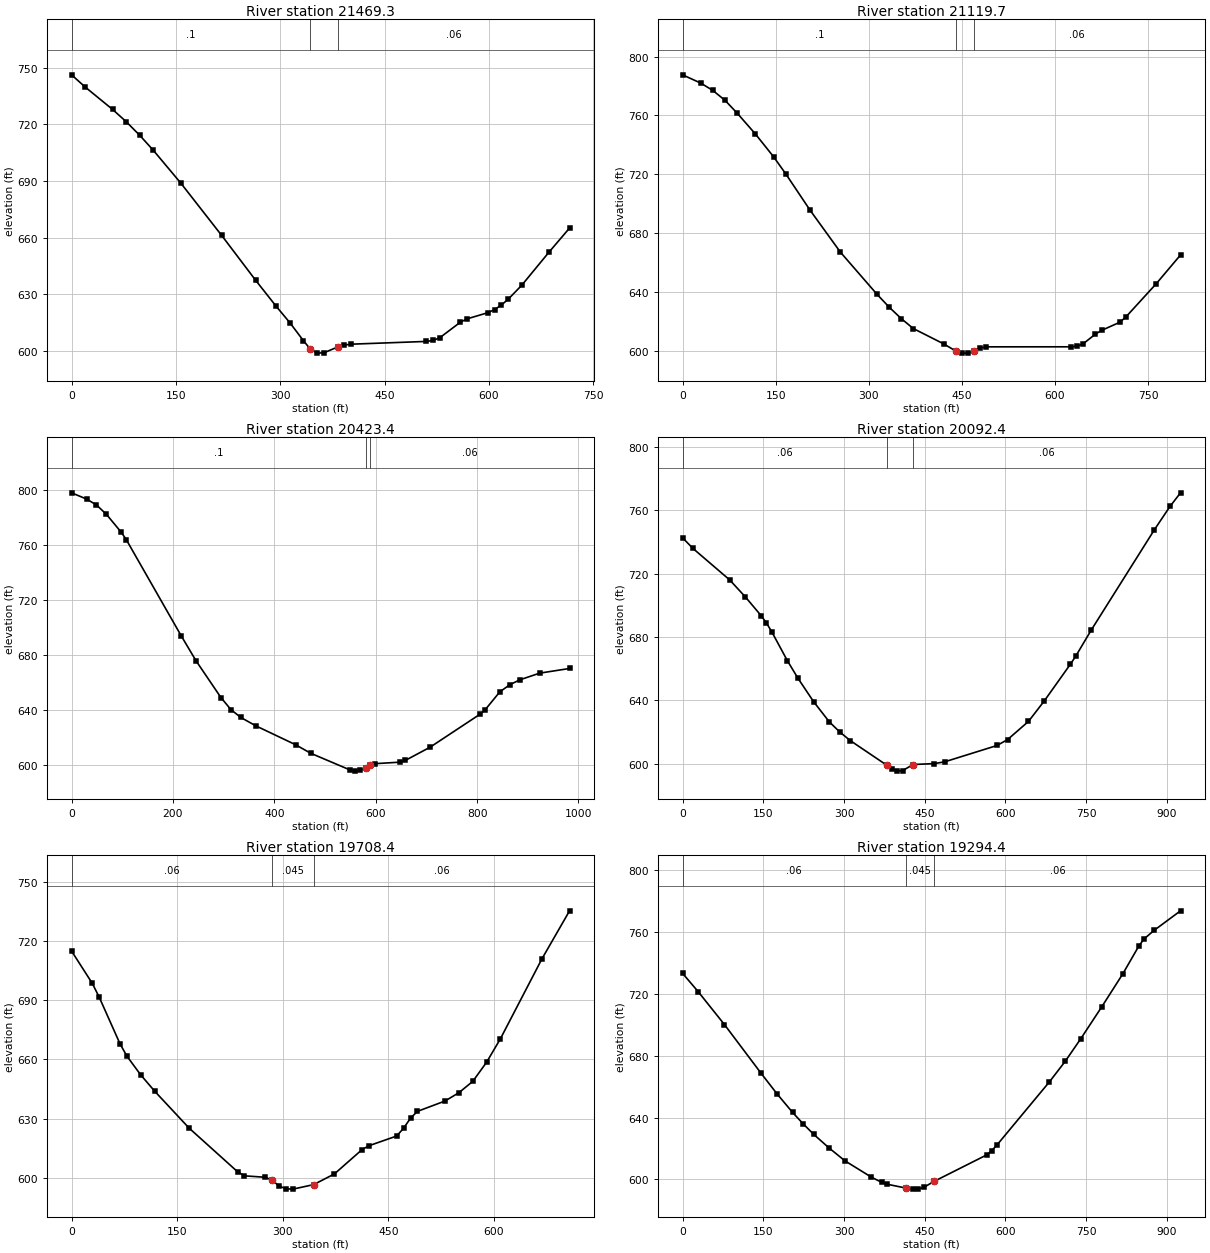
Type RM Length L Ch R = 1 ,21469.3 ,348.9,349.6,350.2
XS GIS Cut Line= 2
     1694971.691      544375.153     1694837.313      545078.511
#Sta/Elev= 30
       0  746.29    19.6  739.81    58.9  727.98    78.5  721.49    98.1  714.22
   117.7  706.25     157  688.97   215.8  661.24   264.8  637.41   294.3  623.64
   313.9     615   333.5  605.41   343.3  601.03   353.1  598.87   362.9  599.05
   382.6  602.11   392.4  603.16   402.2  603.61   510.1  605.07   519.9  605.58
   529.7  607.08   559.1  615.26   568.9  617.04   598.4  620.27   608.2  621.92
     618  624.34   627.8   627.4   647.4  634.84   686.6  652.39   716.1  665.13
#Mann= 3 , 0 , 0
       0      .1       0   343.3    .045       0   382.6     .06       0
Bank Sta=343.3,382.6
XS Rating Curve= 0 ,0
Exp/Cntr=0.3,0.1

Type RM Length L Ch R = 1 ,21119.7 ,726.5,696.2,666
XS GIS Cut Line= 2
      1694662.04      544194.762     1694511.462      544982.913
#Sta/Elev= 30
       0  787.63    29.4     782    48.9  776.98    68.5  770.26    88.1  761.53
   117.4  747.38   146.8  731.83   166.4   720.2   205.5  695.53   254.4  666.96
   313.1  638.41   332.7  629.64   352.3  621.81   371.8     615   420.8  604.56
   440.6 599.602   450.1  598.26   459.9  598.26   469.5 599.769   479.5  601.67
   489.3  602.54   626.3  602.56     636  602.98   645.8  604.71   665.4  611.22
   675.2  613.73   704.6  619.27   714.3  622.84   763.3   645.5   802.4  665.06
#Mann= 3 , 0 , 0
       0      .1       0   440.6    .045       0   469.5     .06       0
Bank Sta=440.6,469.5
XS Rating Curve= 0 ,0
Exp/Cntr=0.3,0.1

Type RM Length L Ch R = 1 ,20423.4 ,333.4,331.1,328.4
XS GIS Cut Line= 2
     1693589.362      544542.194     1694466.289      544985.077
#Sta/Elev= 30
       0  797.73    29.5  793.22    49.1  788.93    68.8  782.08    98.2     769
   108.1  763.61   216.1  693.96   245.6  675.66   294.7  648.97   314.4   640.2
     334   634.5   363.5  628.44   442.1  614.68   471.6  608.54   550.2  596.25
     560  595.53   569.8  596.07   580.5 598.119   589.4  600.05   599.3  600.96
   648.4  602.06   658.2  603.27   707.3  612.92   805.6  636.84   815.4  639.89
   844.9  653.15   864.5  658.29   884.2  661.85   923.5  666.72   982.4  670.11
#Mann= 3 , 0 , 0
       0      .1       0   580.5    .045       0   589.4     .06       0
Bank Sta=580.5,589.4
XS Rating Curve= 0 ,0
Exp/Cntr=0.3,0.1

Type RM Length L Ch R = 1 ,20092.4 ,375.3,384,388.1
XS GIS Cut Line= 2
     1693599.753      544930.059      1694451.33      545291.934
#Sta/Elev= 30
       0  742.69    19.5   735.9    87.7  716.05   116.9  705.27   146.1   693.5
   155.8  688.94   165.6  683.47   194.8  665.09   214.3  654.09   243.5  639.24
   272.7   626.5   292.2  620.07   311.7  614.65   379.8  599.04   389.6  596.75
   399.3  595.38   409.1  595.75   428.6  599.56   467.5  600.12     487  601.24
   584.4  611.57   603.9  615.27   642.8  626.76     672  639.61   720.7  662.87
   730.5  667.88   759.7  684.57   876.6  747.66   905.8  762.48   925.3  771.04
#Mann= 3 , 0 , 0
       0     .06       0   379.8    .045       0   428.6     .06       0
Bank Sta=379.8,428.6
XS Rating Curve= 0 ,0
Exp/Cntr=0.3,0.1

Type RM Length L Ch R = 1 ,19708.4 ,400.7,414,427.3
XS GIS Cut Line= 2
     1693643.514      545224.344     1694273.629      545545.635
#Sta/Elev= 30
       0  714.83    29.5  698.46    39.3  691.48    68.8  667.93    78.6  661.69
    98.2  652.22   117.9  644.02     167  625.28   235.8  603.22   245.6  601.16
   275.1  600.44   284.9  598.95   294.7  596.03   304.5  594.61   314.4  594.44
   343.8  596.72   373.3  602.12   412.6  614.43   422.4  616.39   461.7  621.29
   471.5  625.21   481.4   630.3   491.2  633.76   530.5  639.01   550.1   643.2
   569.8  648.91   589.4  658.57   609.1  670.48     668  710.85   707.3  735.18
#Mann= 3 , 0 , 0
       0     .06       0   284.9    .045       0   343.8     .06       0
Bank Sta=284.9,343.8
XS Rating Curve= 0 ,0
Exp/Cntr=0.3,0.1

Type RM Length L Ch R = 1 ,19294.4 ,294.7,305.3,315
XS GIS Cut Line= 2
     1693428.825      545250.055     1693913.669      546038.131
#Sta/Elev= 30
       0  733.17    29.2  721.24    77.9  700.04   146.1  668.53   175.3  655.43
   204.5   643.3     224     636   243.5  629.23   272.7  620.23   301.9  612.03
   350.6  601.58   370.1  598.14   379.8  596.96     415  594.48   428.6  593.78
   438.3  593.86     448  594.86   467.5   598.8   564.9  615.83   574.6  618.64
   584.4  622.34   681.8  663.09     711  676.28   740.2  691.02   779.2  711.62
   818.1  732.81   847.4  750.48   857.1  755.21   876.6  760.97   925.3  773.49
#Mann= 3 , 0 , 0
       0     .06       0     415    .045       0   467.5     .06       0
Bank Sta=415,467.5
XS Rating Curve= 0 ,0
Exp/Cntr=0.3,0.1

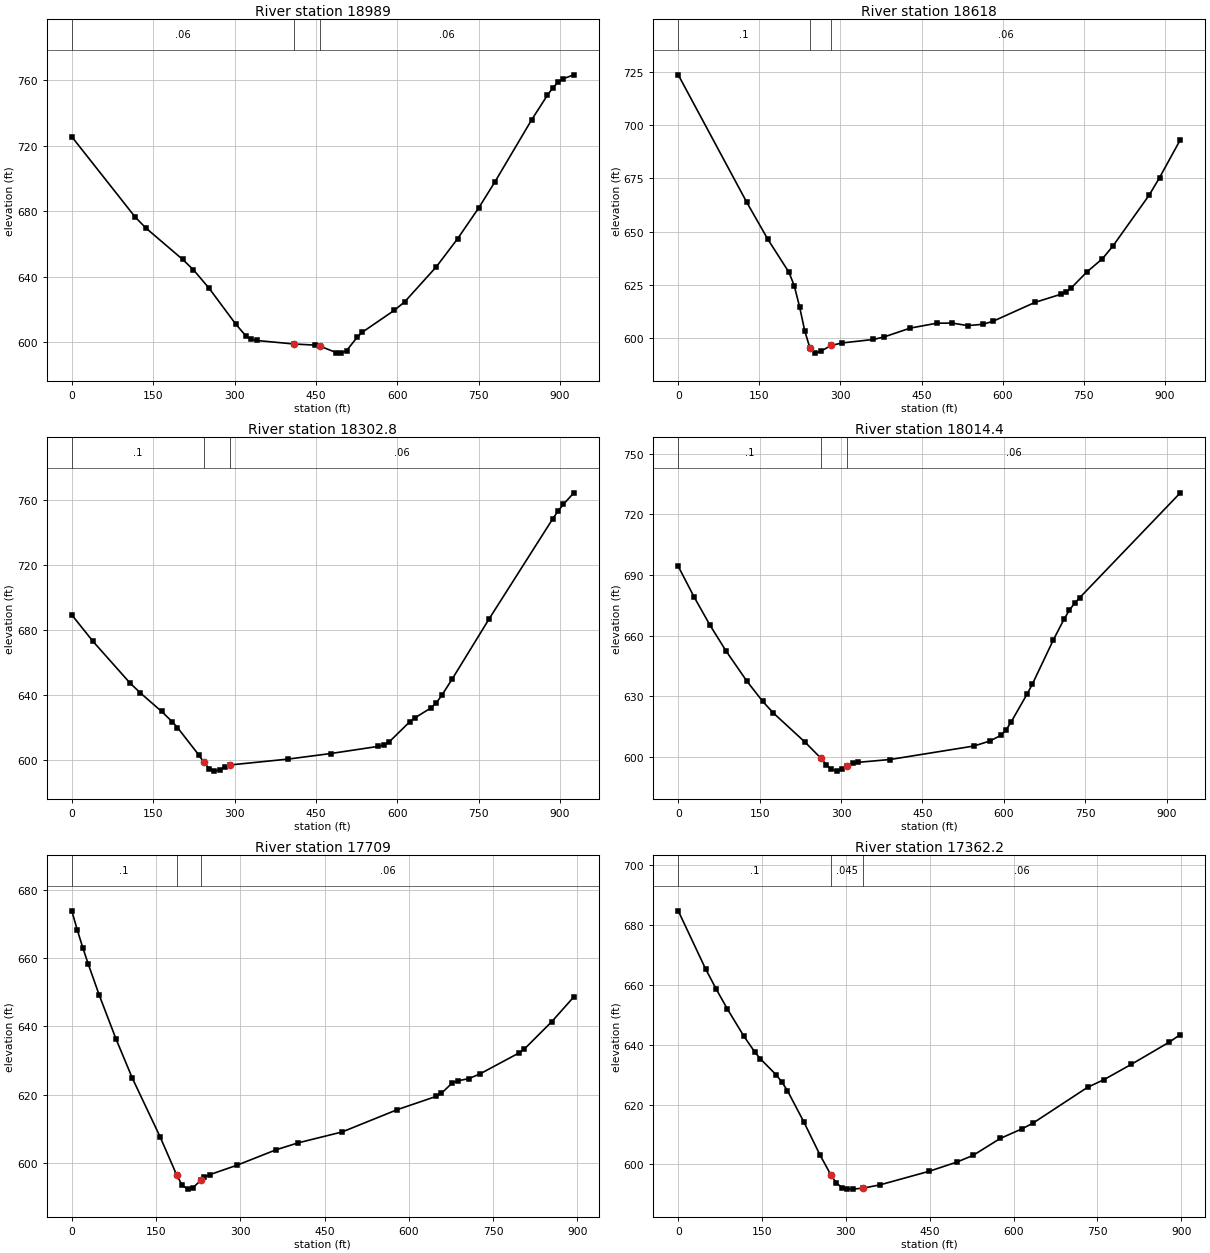
Type RM Length L Ch R = 1 ,18989   ,368.1,371.1,373.2
XS GIS Cut Line= 2
     1693307.227      545280.304     1693465.665      546191.915
#Sta/Elev= 30
       0  725.57   116.9  676.43   136.4   669.8   204.5  650.51     224  644.28
   253.2  632.89   301.9  611.13   321.4  603.59   331.2  601.68   340.9  600.99
     410 598.841     448  598.17   457.8  597.47     487  593.65   496.7  593.27
   506.5  594.83     526  602.96   535.7  606.12   594.1  619.36   613.6  624.64
     672   646.1     711  663.17     750  682.06   779.2   697.6   847.4  735.83
   876.6  750.94   886.3  755.37   896.1   758.8   905.8  761.01   925.3   763.4
#Mann= 3 , 0 , 0
       0     .06       0     410    .045       0   457.8     .06       0
Bank Sta=410,457.8
XS Rating Curve= 0 ,0
Exp/Cntr=0.3,0.1

Type RM Length L Ch R = 1 ,18618   ,317.4,315.2,314.6
XS GIS Cut Line= 4
     1693124.979      545289.711     1693118.082      545767.606
      1693060.93      545888.537     1693111.825      546201.199
#Sta/Elev= 30
       0  723.46   126.8  663.68   165.8  646.35   204.8  630.89   214.6  624.58
   224.3  614.84   234.1   603.3   243.8  595.22   253.6  593.03   263.4  593.88
   282.9  596.62   302.4  597.78   360.9  599.43   380.4   600.6   429.2  604.77
   477.9  607.04   506.6  607.12   535.3  605.93   563.9  606.55     583  608.06
   659.7  616.81   707.7  620.62   717.3  621.72   726.9  623.62   755.7  631.07
   784.5  637.29   803.7  643.16   870.9  667.07   890.1  675.27   928.5  693.04
#Mann= 3 , 0 , 0
       0      .1       0   243.8    .045       0   282.9     .06       0
Bank Sta=243.8,282.9
XS Rating Curve= 0 ,0
Exp/Cntr=0.3,0.1

Type RM Length L Ch R = 1 ,18302.8 ,288.2,288.4,288.2
XS GIS Cut Line= 2
     1692790.538      545320.657     1692873.549      546242.202
#Sta/Elev= 30
       0  689.09      39  672.82   107.1  647.23   126.6  640.99   165.6  629.67
   185.1  623.34   194.8  619.75   233.8     603   243.5  598.37   253.2   594.5
     263  592.94   272.7  593.72   282.4  595.56   292.2  596.75   399.3  600.37
   477.2  603.77   564.9  608.17   574.6  608.96   584.4  610.73   623.3  623.44
   633.1  625.87   662.3   631.9     672  635.08   681.8  639.51   701.3  649.72
   769.4  686.74   886.3  748.13   896.1   752.9   905.8  757.04   925.3  764.18
#Mann= 3 , 0 , 0
       0      .1       0   243.5    .045       0   292.2     .06       0
Bank Sta=243.5,292.2
XS Rating Curve= 0 ,0
Exp/Cntr=0.3,0.1

Type RM Length L Ch R = 1 ,18014.4 ,304.2,305.4,306.6
XS GIS Cut Line= 2
     1692503.258      545328.196     1692586.269      546249.741
#Sta/Elev= 30
       0   694.3    29.2  679.16    58.4   665.2    87.7  652.53   126.6  637.38
   155.8  627.35   175.3  621.64   233.8  607.17     263  599.23   272.7  596.08
   282.4  593.68   292.2  592.84   301.9  593.66   311.4 595.289   321.4  596.64
   331.2   597.2   389.6  598.57   545.4   605.3   574.6   607.8   594.1   610.5
   603.9   613.2   613.6  617.23   642.8  630.98   652.6  635.92   691.5  657.96
     711   668.1   720.7   672.5   730.5  676.05   740.2  678.85   925.3  730.73
#Mann= 3 , 0 , 0
       0      .1       0     263    .045       0   311.4     .06       0
Bank Sta=263,311.4
XS Rating Curve= 0 ,0
Exp/Cntr=0.3,0.1

Type RM Length L Ch R = 1 ,17709   ,331.8,346.8,361.8
XS GIS Cut Line= 2
     1692217.652      545417.913       1692251.4      546310.861
#Sta/Elev= 30
       0  673.92     9.8  668.32    19.6  663.11    29.5  658.22    49.1  649.08
    78.6  636.36     108  624.73   157.1  607.63   186.6  596.43   196.4   593.4
   206.2  592.24     216   592.7     230 594.879   235.7  595.72   245.5  596.48
   294.6  599.29   363.3  603.77   402.6  605.81   481.2  609.02   579.4  615.57
   648.1  619.43   657.9  620.37   677.6  623.47   687.4  624.04     707  624.68
   726.6  626.07   795.4  632.15   805.2   633.3   854.3  641.39   893.6  648.67
#Mann= 3 , 0 , 0
       0      .1       0   186.6    .045       0     230     .06       0
Bank Sta=186.6,230
XS Rating Curve= 0 ,0
Exp/Cntr=0.3,0.1

Type RM Length L Ch R = 1 ,17362.2 ,275.5,282.6,289
XS GIS Cut Line= 2
     1692053.199      545373.346     1691555.099      546120.724
#Sta/Elev= 30
       0  684.77    48.8  665.39    68.3  658.48    87.9  651.94   117.2  642.91
   136.7  637.62   146.4  635.38   175.7  629.83   185.5  627.49   195.2  624.68
   224.5  614.25   253.8  603.05   273.4  596.35   283.1  593.69   292.9  592.24
   302.6  591.78   312.4   591.7   331.2592.0405   361.2  593.14   449.1  597.68
   497.9  600.71   527.2  602.96     576  608.64     615  611.86   634.6  613.77
   732.2  625.74   761.5   628.3   810.3   633.4   878.6  640.88   898.2  643.38
#Mann= 3 , 0 , 0
       0      .1       0   273.4    .045       0   331.2     .06       0
Bank Sta=273.4,331.2
XS Rating Curve= 0 ,0
Exp/Cntr=0.3,0.1