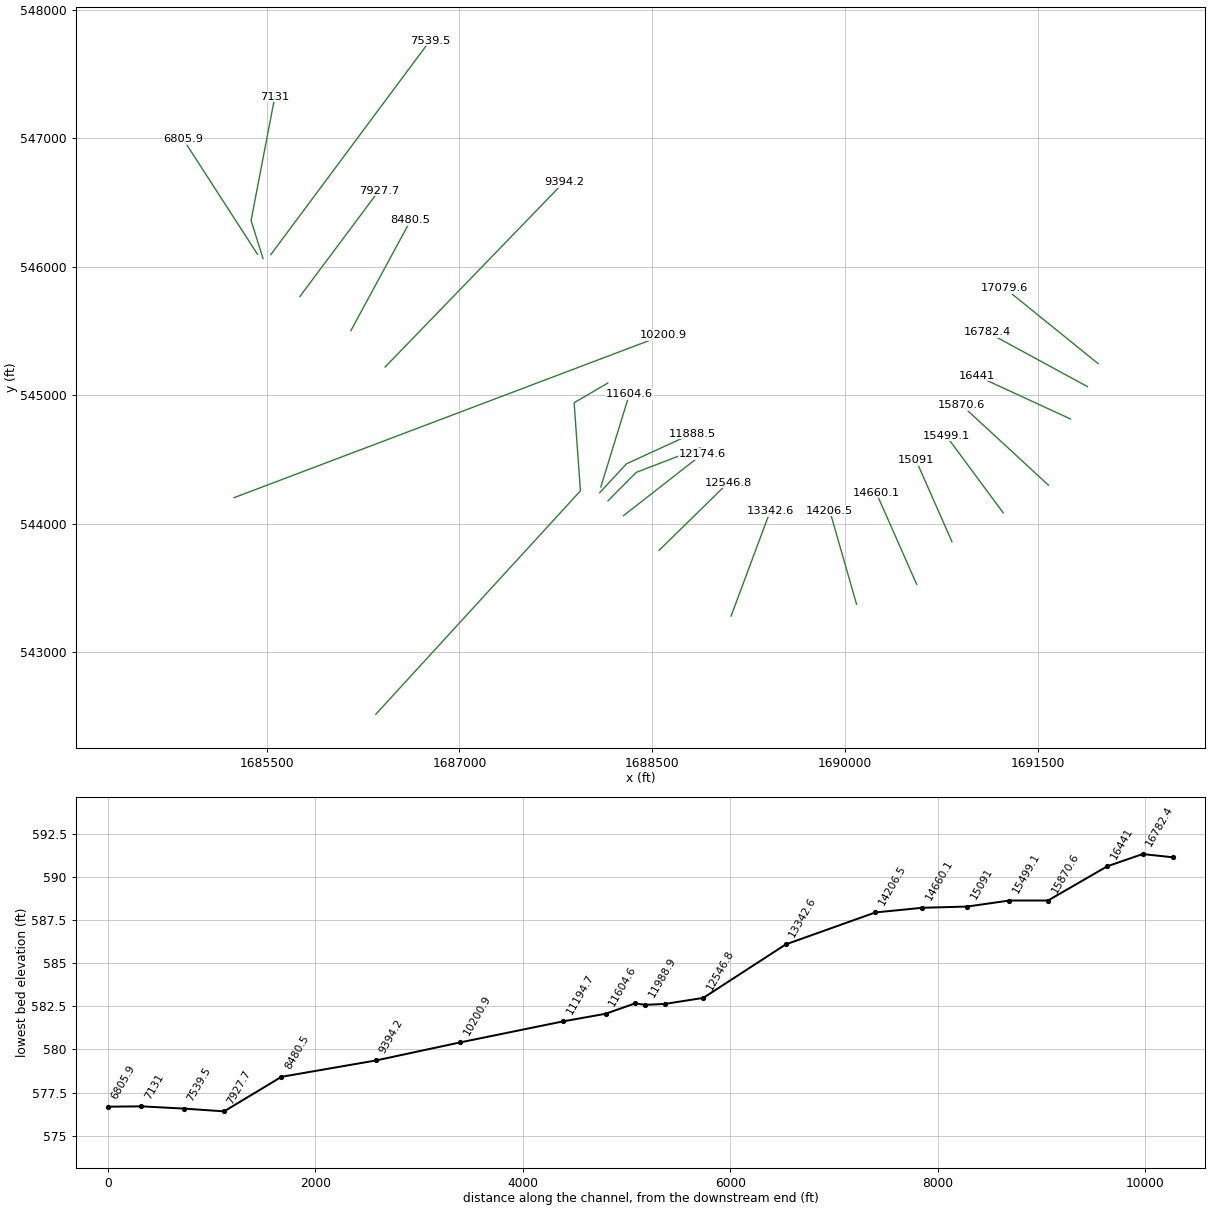
HEC-RAS study PoplarFk.prj: PoplarFk

--- PoplarFk.g01 (geometry) --- (continued)

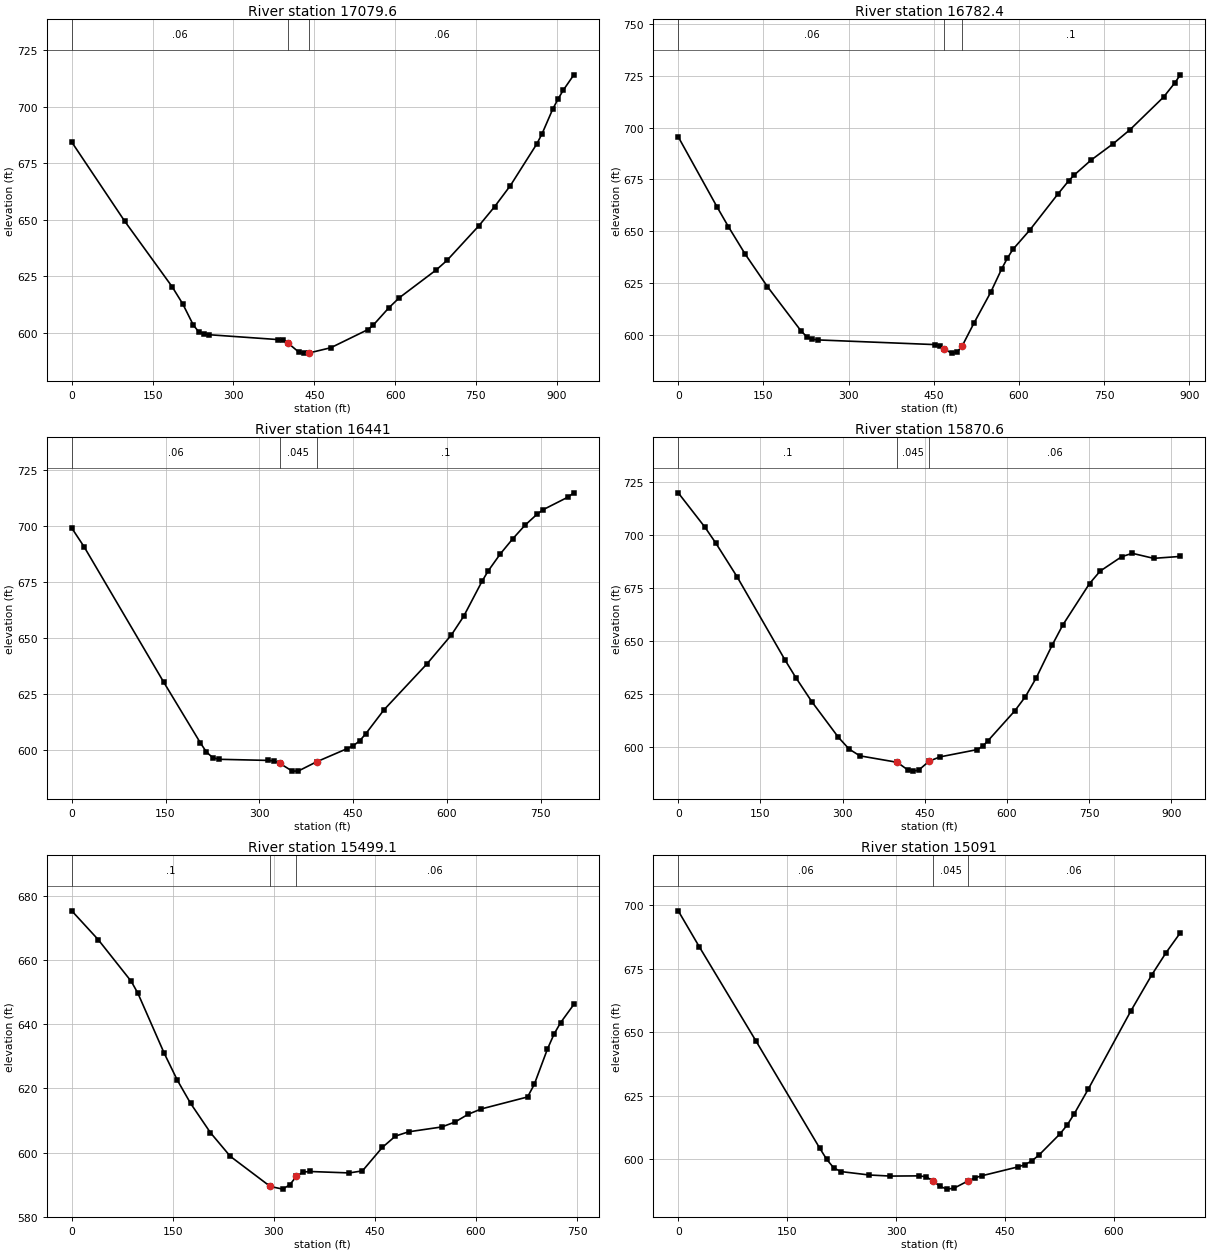
Type RM Length L Ch R = 1 ,17079.6 ,292.8,297.2,299.3
XS GIS Cut Line= 2
     1691966.387      545247.055     1691242.018      545832.986
#Sta/Elev= 30
       0  684.34    98.1  649.45   186.3  620.43     206  612.84   225.6  603.52
   235.4  600.59   245.2  599.54     255  599.25   382.5  597.11   392.3  596.79
   402.1  595.39   421.7   591.5   431.5  591.12   440.9 591.226   480.6   593.5
   549.2  601.48     559  603.37   588.4  611.15     608  615.62   676.7  627.95
   696.3  632.08   755.2  647.31   784.6   655.8     814  665.16     863  683.56
   872.8  688.08   892.4  698.86   902.3  703.35   912.1   707.3   931.7  714.07
#Mann= 3 , 0 , 0
       0     .06       0   402.1    .045       0   440.9     .06       0
Bank Sta=402.1,440.9
XS Rating Curve= 0 ,0
Exp/Cntr=0.3,0.1

Type RM Length L Ch R = 1 ,16782.4 ,340.7,341.4,340.8
XS GIS Cut Line= 2
     1691884.544      545067.491     1691107.575      545489.774
#Sta/Elev= 30
       0  695.55    68.8  661.56    88.4  652.23   117.9  639.03   157.2  623.32
   216.2  602.04     226  599.31   235.8  598.01   245.6  597.68     452  595.42
   461.8  594.58   468.8 593.237   481.5  591.31   491.3   591.9     500 594.705
   520.8  605.75   550.2  620.56   569.9  632.03   579.7  637.08   589.5  641.33
     619  650.56   668.1  667.79   687.8   674.4   697.6   677.2   727.1  684.34
   766.4  692.31   795.9  699.05   854.8  714.71   874.5  721.51   884.3  725.44
#Mann= 3 , 0 , 0
       0     .06       0   468.8    .045       0     500      .1       0
Bank Sta=468.8,500
XS Rating Curve= 0 ,0
Exp/Cntr=0.3,0.1

Type RM Length L Ch R = 1 ,16441   ,568.1,570.5,564.3
XS GIS Cut Line= 2
     1691752.983      544815.524     1691023.669      545151.663
#Sta/Elev= 30
       0  699.18    19.6  690.88   146.9  630.41   205.7  603.22   215.4  599.13
   225.2  596.68     235  595.89   313.4  595.39   323.2  595.16     333  594.02
   352.6   590.6   362.4  590.66   391.7  594.78   440.7  600.68   450.5  602.02
   460.3  604.09   470.1  607.25   499.5  618.04     568  638.49   607.2  651.45
   626.8  659.76   656.2  675.42   665.9  679.99   685.5  687.68   705.1  694.32
   724.7   700.4   744.3   705.4   754.1  707.42   793.3  712.97     803  714.92
#Mann= 3 , 0 , 0
       0     .06       0     333    .045       0   391.7      .1       0
Bank Sta=333,391.7
XS Rating Curve= 0 ,0
Exp/Cntr=0.3,0.1

Type RM Length L Ch R = 1 ,15870.6 ,381.4,371.5,367.4
XS GIS Cut Line= 2
     1691580.952      544301.154     1690907.083      544922.697
#Sta/Elev= 30
       0  719.99    48.8  703.75    68.3  696.38   107.3  680.42     195  641.07
   214.6   632.8   243.8  621.44   292.6  604.52   312.1  599.01   331.6  595.84
   399.9  592.78   419.4  589.14   429.1  588.62   438.9  589.07   458.4  593.36
   477.9  595.34   546.1  598.79   555.9  600.41   565.6  602.98   614.4  617.05
   633.9  623.78   653.4  632.52   682.7  648.08   702.2  657.63     751  677.18
   770.4  683.05   809.5  689.82     829  691.44     868  689.06   916.7  689.97
#Mann= 3 , 0 , 0
       0      .1       0   399.9    .045       0   458.4     .06       0
Bank Sta=399.9,458.4
XS Rating Curve= 0 ,0
Exp/Cntr=0.3,0.1

Type RM Length L Ch R = 1 ,15499.1 ,413.7,408.1,402.4
XS GIS Cut Line= 2
     1691229.577      544085.287     1690786.303      544684.436
#Sta/Elev= 30
       0  675.37    39.2   666.4    88.3  653.38    98.1   649.7   137.3  630.94
   156.9   622.5   176.5  615.32   205.9   606.2   235.4  598.83   294.6 589.457
   313.1  588.62   323.6  589.97   333.4  592.59   343.2  593.92     353  594.12
   411.9  593.67   431.5  594.31   460.9   601.6   480.5  605.16   500.1  606.49
   549.2     608   568.8  609.52   588.4  611.95     608  613.62   676.6  617.35
   686.5  621.24   706.1  632.28   715.9  636.94   725.7  640.54   745.3  646.19
#Mann= 3 , 0 , 0
       0      .1       0   294.6    .045       0   333.4     .06       0
Bank Sta=294.6,333.4
XS Rating Curve= 0 ,0
Exp/Cntr=0.3,0.1

Type RM Length L Ch R = 1 ,15091   ,430,430.9,431.7
XS GIS Cut Line= 2
     1690830.314      543861.933     1690550.838      544494.557
#Sta/Elev= 30
       0   697.9    29.2  683.64   107.2  646.57   194.8  604.45   204.6  599.96
   214.3  596.61     224  595.19     263  593.84   292.2  593.41   331.2  593.49
   340.9  593.18   350.7  591.58   360.4  589.36   370.2  588.27   379.9  588.64
   399.4  591.53   409.1  592.76   418.9  593.58   467.6     597   477.3  597.87
     487  599.38   496.8  601.66     526  610.07   535.8  613.54   545.5  617.94
     565  627.76   623.4  658.42   652.6  672.81   672.1  681.47   691.6  689.25
#Mann= 3 , 0 , 0
       0     .06       0   350.7    .045       0   399.4     .06       0
Bank Sta=350.7,399.4
XS Rating Curve= 0 ,0
Exp/Cntr=0.3,0.1

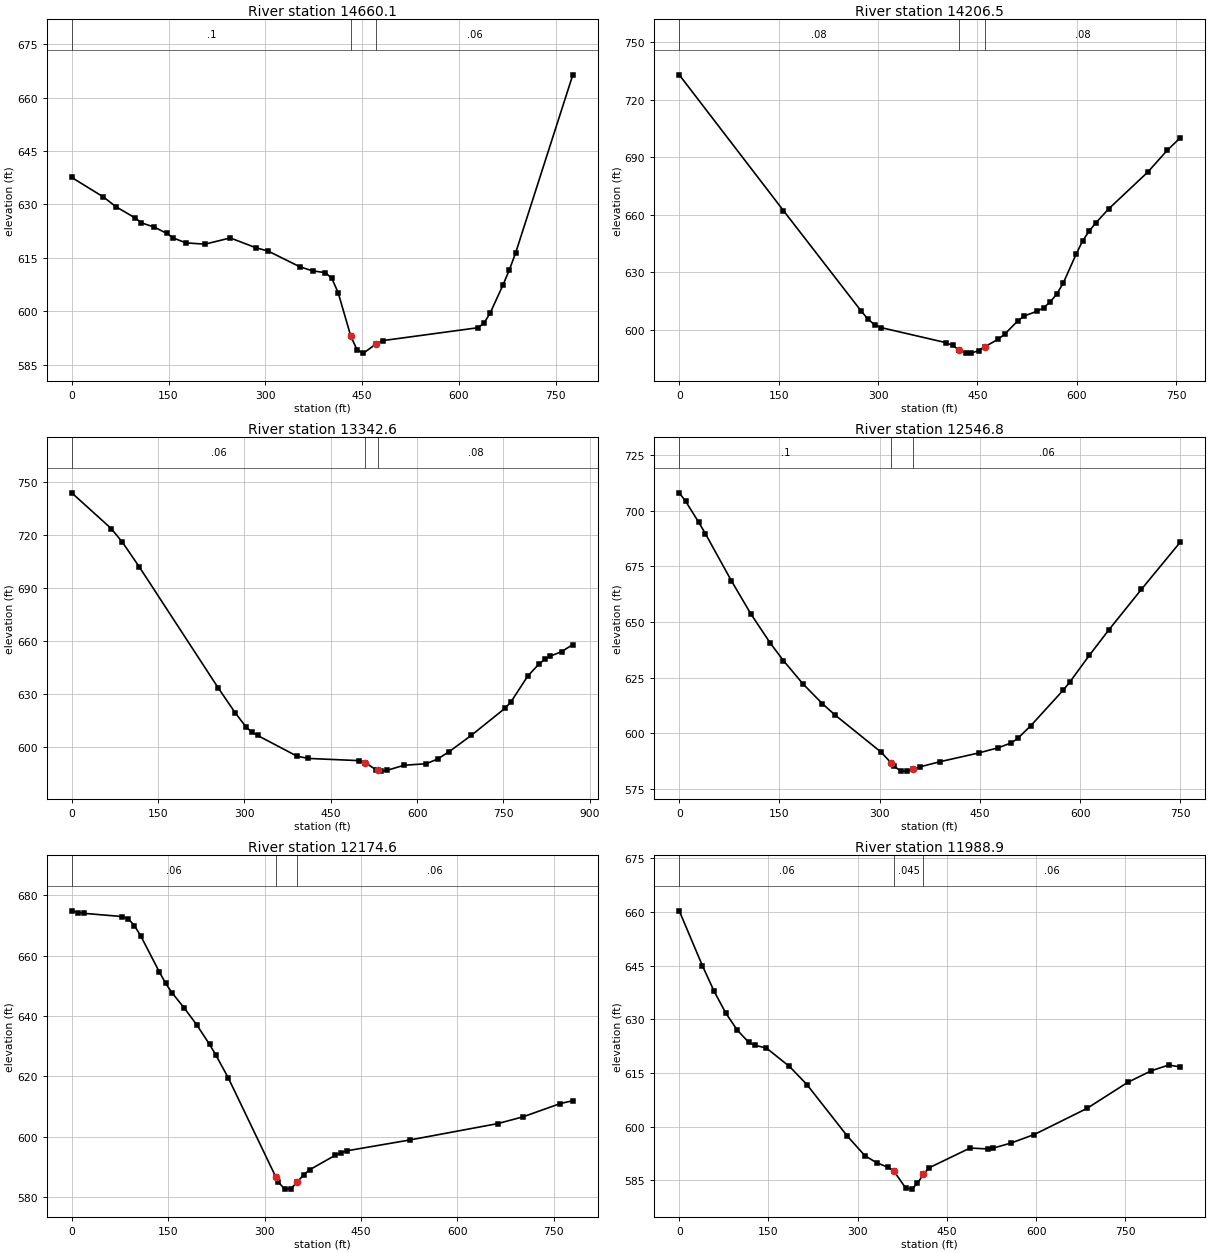
Type RM Length L Ch R = 1 ,14660.1 ,457.1,453.6,450
XS GIS Cut Line= 2
     1690555.671      543530.723     1690241.896      544240.986
#Sta/Elev= 30
       0   637.6    49.1  632.11    68.8  629.34    98.3  626.21   108.1  624.83
   127.8  623.64   147.4  621.87   157.3  620.59   176.9  619.21   206.4  618.84
   245.7  620.59     285  617.86   304.7  616.87   353.8  612.45   373.5  611.33
   393.2  610.82     403  609.22   412.8  605.24   432.5  592.93   442.3  589.08
   452.1   588.2   471.8  590.81   481.6  591.71     629  595.33   638.9  596.62
   648.7   599.6   668.4  607.41   678.2  611.64     688  616.45   776.5  666.46
#Mann= 3 , 0 , 0
       0      .1       0   432.5    .045       0   471.8     .06       0
Bank Sta=432.5,471.8
XS Rating Curve= 0 ,0
Exp/Cntr=0.3,0.1

Type RM Length L Ch R = 1 ,14206.5 ,881.9,863.9,843.2
XS GIS Cut Line= 2
     1690088.383      543374.924     1689879.924      544101.679
#Sta/Elev= 30
       0  733.09   157.1  662.32   274.9   609.7   284.8  605.66   294.6  602.76
   304.4  601.25   402.6  593.38   412.4  591.91   422.4 589.547     432  587.95
   440.8  587.93   451.7  589.29   461.5  591.33   481.1  595.17     491  597.78
   510.6  604.72   520.4   607.3     540   609.8   549.9  611.62   559.7  614.62
   569.5  618.71   579.3  624.41     599  639.67   608.8  646.56   618.6  651.65
   628.4  655.81     648  663.19     707  682.38   736.4  693.77   756.1  700.28
#Mann= 3 , 0 , 0
       0     .08       0   422.4    .045       0   461.5     .08       0
Bank Sta=422.4,461.5
XS Rating Curve= 0 ,0
Exp/Cntr=0.3,0.1

Type RM Length L Ch R = 1 ,13342.6 ,803.2,795.7,785
XS GIS Cut Line= 2
     1689112.372      543282.877     1689416.607       544098.54
#Sta/Elev= 30
       0  743.59    68.5   723.4      88  715.66   117.4  701.67   254.3  633.28
   283.7  619.24   303.2  610.93     313  608.19   322.8  606.29   391.3  594.56
   410.8  593.27   498.9  592.02   510.3  590.84   528.2  586.93   532.3 586.574
     538  586.08   547.8  586.53   577.1  589.39   616.2  590.28   635.8  592.95
   655.4  597.01   694.5  606.39   753.2  621.76     763  625.22   792.3  639.88
   811.9  646.73   821.6  649.31   831.4  651.16     851  653.68   870.6  657.73
#Mann= 3 , 0 , 0
       0     .06       0   510.3    .045       0   532.3     .08       0
Bank Sta=510.3,532.3
XS Rating Curve= 0 ,0
Exp/Cntr=0.3,0.1

Type RM Length L Ch R = 1 ,12546.8 ,375.4,372.2,368
XS GIS Cut Line= 2
     1688553.072      543795.169     1689089.304       544319.67
#Sta/Elev= 30
       0  707.98     9.7   704.1    29.2  694.73      39   689.7    77.9  668.55
   107.2  653.59   136.4  640.41   155.9  632.63   185.1  622.19   214.3  613.25
   233.8  608.04     302  591.54   317.5  586.55   321.5  585.25   331.2  583.05
     341  582.98   350.2583.7957   360.4   584.9   389.7  587.17   448.1  591.13
   477.3  593.46   496.8  595.64   506.6  597.66     526  603.32   574.8  619.36
   584.5  622.93   613.7  634.93   642.9  646.37   691.6  664.56   750.1  685.88
#Mann= 3 , 0 , 0
       0      .1       0   317.5    .045       0   350.2     .06       0
Bank Sta=317.5,350.2
XS Rating Curve= 0 ,0
Exp/Cntr=0.3,0.1

Type RM Length L Ch R = 1 ,12174.6 ,192.3,185.7,178.9
XS GIS Cut Line= 2
     1688275.465      544063.484     1688889.649      544543.385
#Sta/Elev= 30
       0  674.81     9.7  674.23    19.5  673.97    77.9  672.92    87.7   672.2
    97.4  669.94   107.2  666.56   136.4  654.52   146.2  650.75   155.9  647.68
   175.4  642.52   194.9  636.92   214.4  630.56   224.1  627.06   243.6  619.44
   317.3  586.71   321.5  584.92   331.3  582.63     341  582.79   350.2584.8271
   360.5  587.35   370.2  589.06   409.2  593.77     419  594.72   428.7  595.35
   526.1  598.92   662.5  604.33   701.5  606.55     760  610.98   779.4  611.91
#Mann= 3 , 0 , 0
       0     .06       0   317.3    .045       0   350.2     .06       0
Bank Sta=317.3,350.2
XS Rating Curve= 0 ,0
Exp/Cntr=0.3,0.1

Type RM Length L Ch R = 1 ,11988.9 ,99,100.5,102
XS GIS Cut Line= 3
     1688155.384      544179.545     1688375.413      544400.866
     1688870.583      544591.041
#Sta/Elev= 30
       0  660.33      39  644.97    58.5   637.9      78  631.83    97.5  627.01
     117  623.57   126.8  622.77   146.3  622.02   185.3  616.85   214.6   611.8
   282.8  597.35   312.1  591.92   331.7  589.97   351.4  588.65   361.2  587.53
   380.8  582.87   390.7  582.58   400.5  584.18   410.3   586.7   420.1  588.54
   488.9  594.06   518.4  593.81   528.2  594.05   557.6  595.45     597  597.84
   685.4  605.12   754.1  612.42   793.4  615.63   822.9  617.24   842.5  616.72
#Mann= 3 , 0 , 0
       0     .06       0   361.2    .045       0   410.3     .06       0
Bank Sta=361.2,410.3
XS Rating Curve= 0 ,0
Exp/Cntr=0.3,0.1

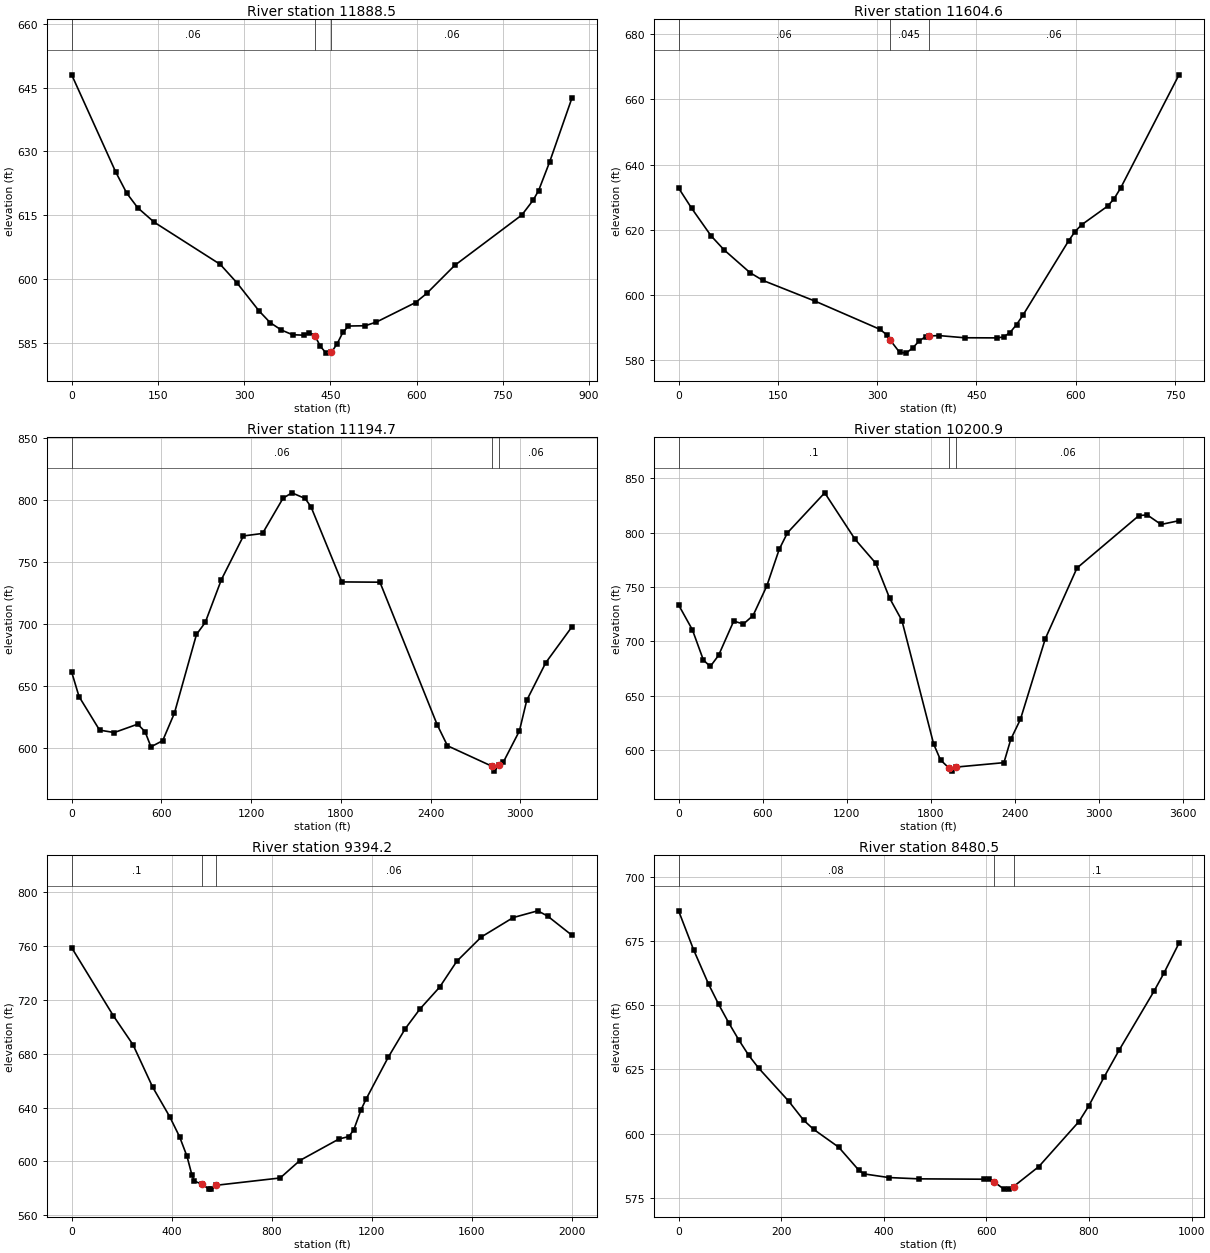
Type RM Length L Ch R = 1 ,11888.5 ,268,283.9,295.4
XS GIS Cut Line= 3
     1688090.579      544242.181     1688298.611      544466.991
     1688811.293      544702.384
#Sta/Elev= 30
       0  647.98    76.6  625.17    95.7  620.22   114.9  616.77   143.6  613.38
   258.4  603.49   287.2   599.2   325.8  592.58   345.2  589.82   364.6  588.09
   384.1  586.98   403.6  586.87   413.3  587.47     423  586.74   432.7  584.24
   442.5  582.66   451.6  582.81   461.9   584.9   471.6  587.51   481.4  589.02
   510.6  589.09     530  589.95   598.1  594.53   617.5  596.67   666.2  603.25
   782.9  615.07   802.4  618.51   812.1  620.79   831.5  627.59   870.4  642.64
#Mann= 3 , 0 , 0
       0     .06       0     423    .045       0   451.6     .06       0
Bank Sta=423,451.6
XS Rating Curve= 0 ,0
Exp/Cntr=0.3,0.1

Type RM Length L Ch R = 1 ,11604.6 ,397.8,409.8,423.9
XS GIS Cut Line= 2
     1688099.335      544287.358     1688321.955      545009.865
#Sta/Elev= 30
       0  632.78    19.6  626.59    49.1  618.08    68.7  613.78     108  606.76
   127.6  604.38   206.2  598.03   304.4  589.35   314.2  587.72   319.2 586.184
   333.8  582.34   343.6  582.06   353.5  583.61   363.3  585.76   373.1  587.12
   378.1 587.314   392.7  587.46     432  586.78   481.1  586.74   490.9  587.02
   500.7  588.37   510.6  590.83   520.4  593.76   589.1  616.51   598.9  619.39
   608.8  621.47     648  627.19   657.8  629.44   667.7  632.72     756  667.55
#Mann= 3 , 0 , 0
       0     .06       0   319.2    .045       0   378.1     .06       0
Bank Sta=319.2,378.1
XS Rating Curve= 0 ,0
Exp/Cntr=0.3,0.1

Type RM Length L Ch R = 1 ,11194.7 ,1025.3,993.9,960.4
XS GIS Cut Line= 4
     1686349.608      542519.531       1687940.7      544256.973
     1687891.664      544942.507     1688153.547      545095.251
#Sta/Elev= 30
       0  661.38    49.1   641.7   186.5  614.67   284.7  612.71   441.7  619.48
   490.8  613.36   530.1  601.19   608.6  606.16   687.1  628.38   834.4  691.72
   893.3  701.45  1001.3  735.97  1148.5  771.11  1276.1  773.12  1413.5  801.51
  1472.4  805.85  1560.8  801.33    1600  794.69  1806.2  734.07  2061.4  733.85
  2444.3     619    2513  602.06  2807.7585.7117  2827.2  581.62  2856.6  586.51
  2886.1  588.76  2994.1  614.01  3043.2  638.68  3170.3  668.96  3346.4  698.06
#Mann= 3 , 0 , 0
       0     .06       0  2807.7    .045       0  2856.6     .06       0
Bank Sta=2807.7,2856.6
XS Rating Curve= 0 ,0
Exp/Cntr=0.3,0.1

Type RM Length L Ch R = 1 ,10200.9 ,795.2,806.7,818.2
XS GIS Cut Line= 2
     1685246.782      544203.898     1688586.142      545467.715
#Sta/Elev= 30
       0  733.54    98.4   710.6     177  682.71   226.2  676.81   285.2  687.03
   393.4  718.66   462.3   715.9   531.2   723.7   629.5  751.01     718  784.75
     777     800  1042.6  836.78    1259     794  1406.6  771.95  1504.9  739.95
  1593.4  719.15  1819.7  605.45  1868.9  590.68  1927.9  583.42  1947.6   580.4
  1977.1   584.1  2321.3   588.2  2370.5  609.76  2439.4  628.22  2616.4   702.3
  2842.6  767.51  3285.3  815.88  3344.3  816.39  3442.6  807.64  3570.5   811.1
#Mann= 3 , 0 , 0
       0      .1       0  1927.9    .045       0  1977.1     .06       0
Bank Sta=1927.9,1977.1
XS Rating Curve= 0 ,0
Exp/Cntr=0.3,0.1

Type RM Length L Ch R = 1 ,9394.2  ,887.7,913.6,937.1
XS GIS Cut Line= 2
     1686421.636      545220.148     1687813.007      546658.413
#Sta/Elev= 30
       0  758.88   166.8  708.22   245.2  686.76   323.7  655.27   392.4  633.09
   431.6  618.25     461  603.83   480.7  589.95   490.5  585.35   519.9  583.11
   549.3  579.36   559.1  579.36   578.8  582.24   833.8  587.66   912.3  600.63
  1069.2  616.68  1108.5  618.44  1128.1  623.56  1157.5  638.54  1177.1  646.23
  1265.4  677.26  1334.1  698.72  1392.9  713.36  1471.4  729.54  1540.1  748.82
  1638.2  766.89  1765.7  781.31  1863.8  786.31    1903  782.45  2001.1  768.04
#Mann= 3 , 0 , 0
       0      .1       0   519.9    .045       0   578.8     .06       0
Bank Sta=519.9,578.8
XS Rating Curve= 0 ,0
Exp/Cntr=0.3,0.1

Type RM Length L Ch R = 1 ,8480.5  ,556.7,552.8,547.3
XS GIS Cut Line= 2
     1686155.502      545503.457     1686620.193      546360.992
#Sta/Elev= 30
       0  686.73    29.3  671.54    58.5  658.17      78  650.36    97.5  643.22
     117   636.6   136.6  630.52   156.1   625.5   214.6  612.65   243.8  605.22
   263.3  601.67   312.1  594.73   351.1  585.82   360.9  584.35   409.6  582.92
   468.2  582.41     595  582.27   604.7  582.18   614.5  581.32     634  578.41
   643.7  578.43     653 579.426   702.2  587.19   780.3  604.68   799.8  610.88
     829  621.88   858.3  632.37   926.6  655.42   946.1  662.51   975.4  674.15
#Mann= 3 , 0 , 0
       0     .08       0   614.5    .045       0     653      .1       0
Bank Sta=614.5,653
XS Rating Curve= 0 ,0
Exp/Cntr=0.3,0.1

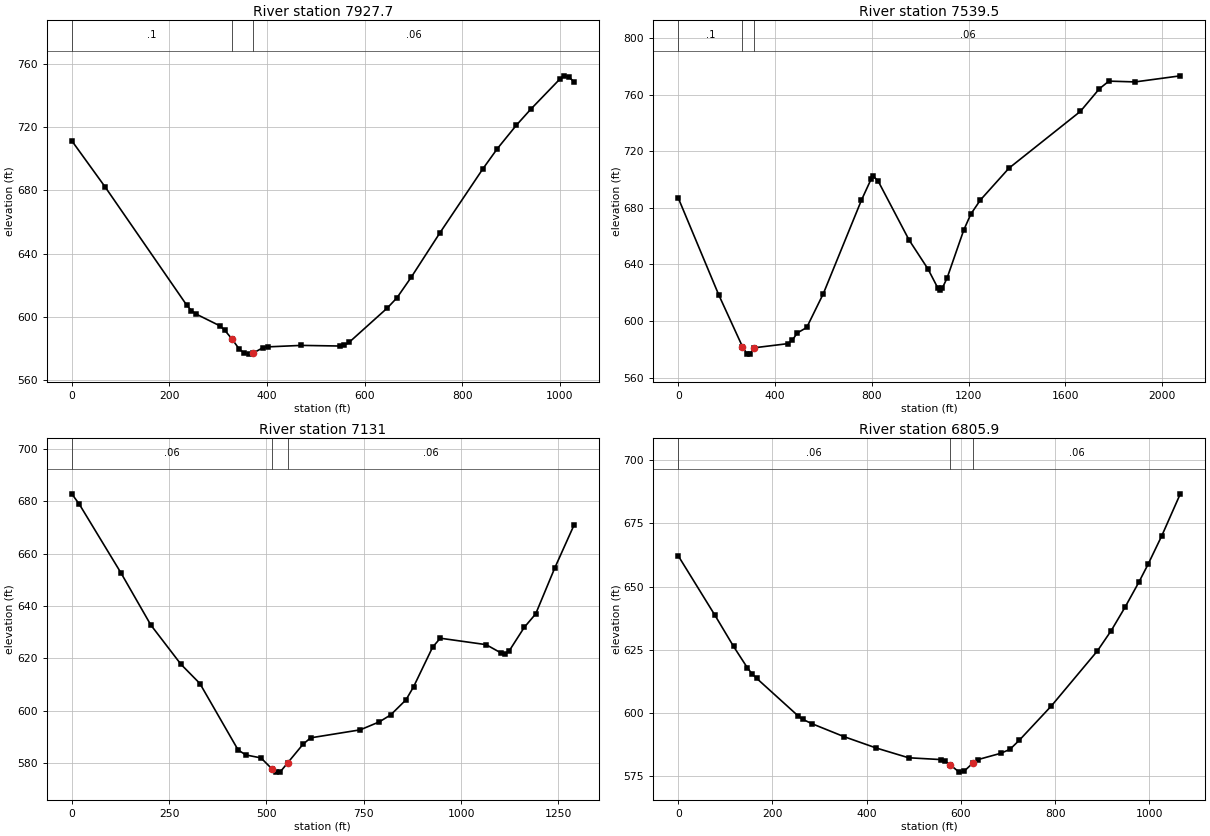
Type RM Length L Ch R = 1 ,7927.7  ,388,388.2,388.1
XS GIS Cut Line= 2
     1685758.409      545768.143     1686373.792      546592.274
#Sta/Elev= 30
       0  711.45    68.6   682.1   235.1  607.57   244.9  603.99   254.7  601.78
   303.7  594.27   313.5  591.48     328  586.04   342.8  579.73   352.6  577.17
   362.4  576.41   372.2  577.19   391.8  580.51   401.6     581   470.2  581.94
   548.6  581.54   558.4     582   568.1  583.86   646.5  605.64   666.1  612.05
   695.5  625.13   754.3  653.25   842.4   693.8   871.8  706.46     911  721.38
   940.4  731.45   999.2  750.28    1009  752.54  1018.7  751.74  1028.5  748.81
#Mann= 3 , 0 , 0
       0      .1       0     328    .045       0   372.2     .06       0
Bank Sta=328,372.2
XS Rating Curve= 0 ,0
Exp/Cntr=0.3,0.1

Type RM Length L Ch R = 1 ,7539.5  ,397.3,408.6,418.5
XS GIS Cut Line= 2
     1685532.702      546094.479     1686770.875      547758.843
#Sta/Elev= 30
       0  687.08   167.1   618.6   265.4  581.84   285.1  576.57   294.9  576.62
   314.6  581.07   452.2  583.97   471.9  586.53   491.6  591.52   530.9  595.42
   599.7  619.44     757  685.52   796.3  700.17   806.2  702.42   825.8  699.04
   953.6  657.36  1032.3  636.68  1071.6  623.65  1081.4  621.85  1091.3  623.37
  1110.9  630.44  1179.8  664.42  1209.2  675.73  1248.6  685.65  1366.6  708.15
  1661.5   748.3  1740.2  764.35  1779.5  769.71  1887.6  769.15  2074.4  773.46
#Mann= 3 , 0 , 0
       0      .1       0   265.4    .045       0   314.6     .06       0
Bank Sta=265.4,314.6
XS Rating Curve= 0 ,0
Exp/Cntr=0.3,0.1

Type RM Length L Ch R = 1 ,7131    ,303.6,325.1,346.7
XS GIS Cut Line= 3
     1685472.046      546064.247      1685379.04      546359.481
     1685563.895      547322.187
#Sta/Elev= 30
       0  682.75    19.4  678.78   125.8  652.76   203.1  632.76   280.5  617.79
   329.1  610.47   427.2  585.18   446.8  583.26     486  582.12     515 577.831
   525.2   576.7     535   576.7   554.6  580.23   593.8  587.27   613.4  589.76
   740.9  592.81   789.9  595.84   819.3  598.51   858.5  604.23   878.1  609.22
   927.1  624.35   946.7  627.73  1064.4  625.28  1103.6  622.04  1113.4  621.79
  1123.2  622.78  1162.4  631.86  1191.8     637  1240.8   654.5  1289.8  670.69
#Mann= 3 , 0 , 0
       0     .06       0     515    .045       0   554.6     .06       0
Bank Sta=515,554.6
XS Rating Curve= 0 ,0
Exp/Cntr=0.3,0.1

Type RM Length L Ch R = 1 ,6805.9  ,511.7,531.4,549.9
XS GIS Cut Line= 2
     1685429.349      546096.682     1684851.115      546991.616
#Sta/Elev= 30
       0  662.18    78.2  638.59   117.3   626.4   146.6  617.96   156.4  615.59
   166.2  613.79   254.2  598.94   263.9  597.58   283.5  595.84   351.9   590.7
   420.3  586.21   488.8  582.36   557.2  581.64     567  580.92   576.7  579.61
   596.3  576.68   606.1  576.94   625.6  580.33   635.4   581.6   684.3  584.12
   703.8  585.67   723.4   589.2   791.8  602.83   889.5  624.58   918.9  632.62
   948.2  641.86   977.5  651.74   997.1  658.84  1026.4  670.18  1065.5  686.68
#Mann= 3 , 0 , 0
       0     .06       0   576.7    .045       0   625.6     .06       0
Bank Sta=576.7,625.6
XS Rating Curve= 0 ,0
Exp/Cntr=0.3,0.1