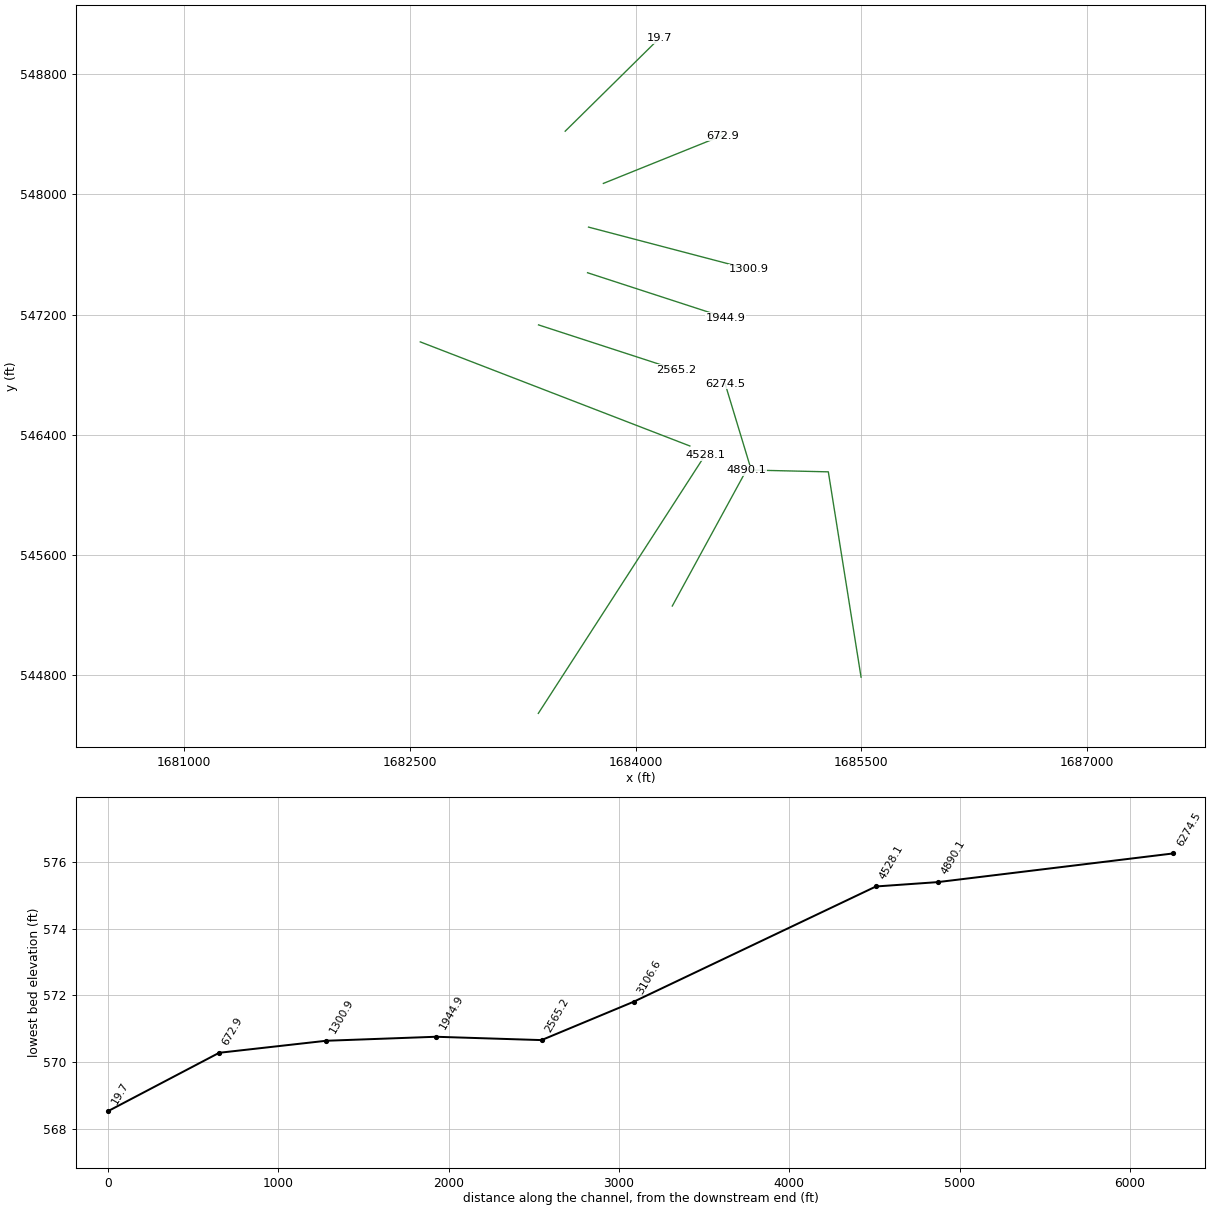
HEC-RAS study PoplarFk.prj: PoplarFk

--- PoplarFk.g01 (geometry) --- (continued)

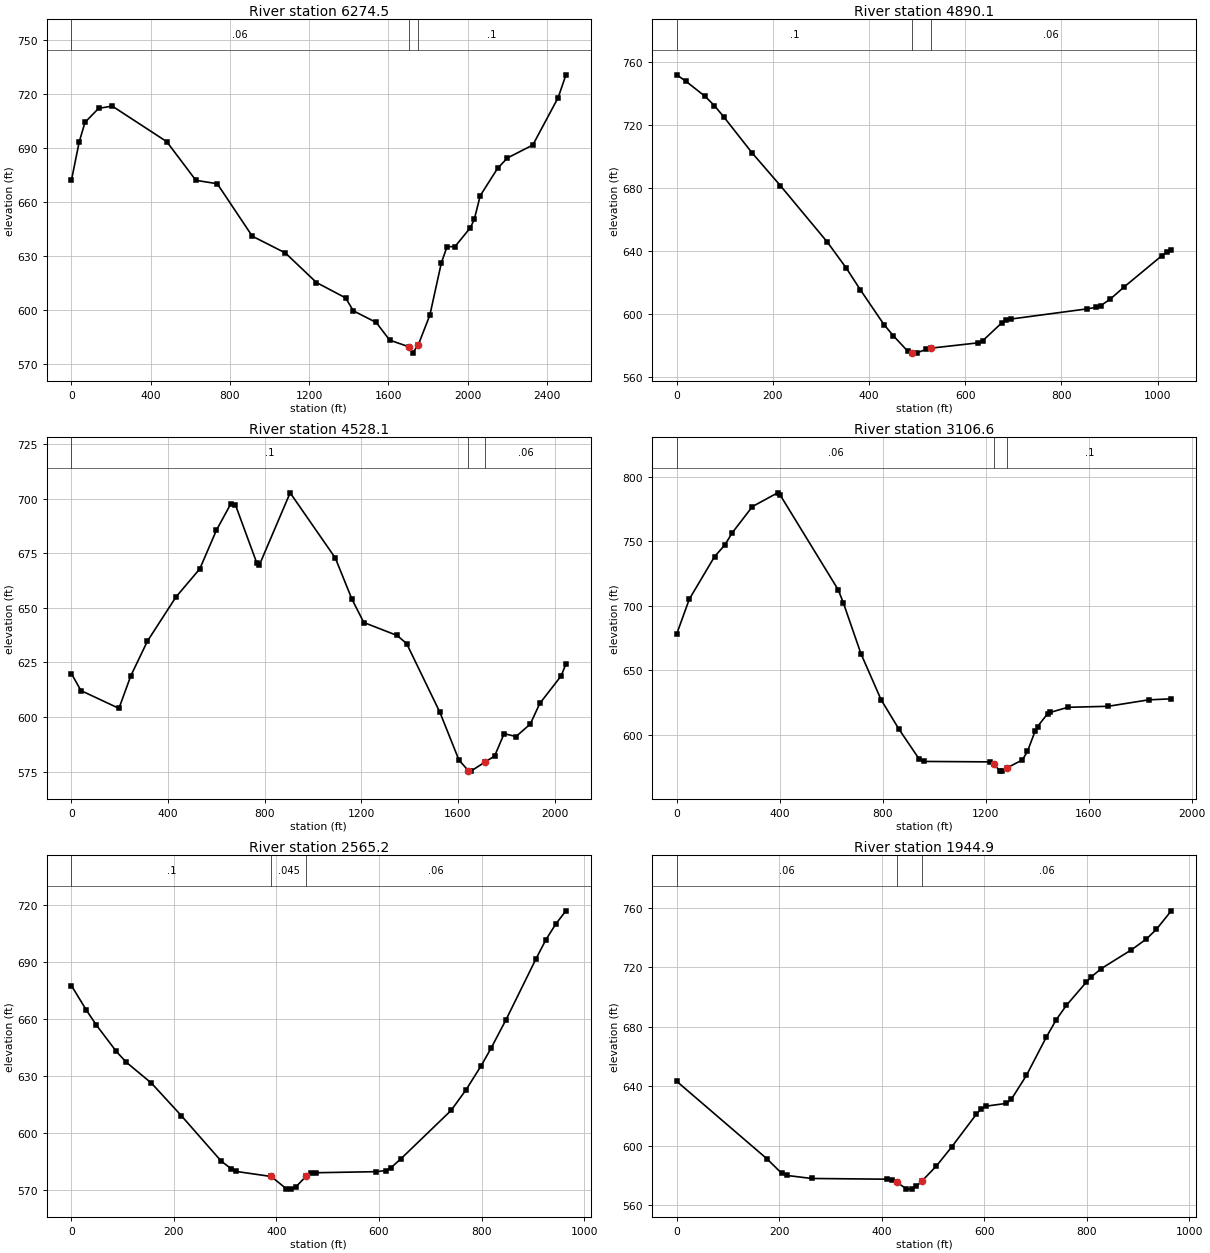
Type RM Length L Ch R = 1 ,6274.5  ,1430.3,1384.4,1336.2
XS GIS Cut Line= 4
     1685498.538      544785.658     1685281.056      546152.869
     1684769.058      546164.871     1684595.392      546739.201
#Sta/Elev= 30
       0     672    39.3   693.3    68.7  704.26   137.5  711.99   206.2  713.25
   481.1  693.55   628.4  672.08   736.4   670.2   913.1  641.11    1080  631.81
  1237.1  615.41  1384.4  606.87    1423  599.74    1539  593.24  1606.6  583.47
  1703.3  579.77  1722.6  576.25  1751.6  580.95  1809.6  597.33  1867.6  626.33
  1896.5   635.3  1935.9  635.27  2014.6  645.87  2034.2  650.56  2063.8  663.55
  2152.3  678.86  2201.5  684.49  2329.3  691.67  2457.2  717.94  2496.6  730.59
#Mann= 3 , 0 , 0
       0     .06       0  1703.3    .045       0  1751.6      .1       0
Bank Sta=1703.3,1751.6
XS Rating Curve= 0 ,0
Exp/Cntr=0.3,0.1

Type RM Length L Ch R = 1 ,4890.1  ,363.7,362,360.3
XS GIS Cut Line= 2
     1684244.355      545259.539      1684736.09      546162.912
#Sta/Elev= 30
       0  752.12    19.6  747.93    58.8  738.49    78.4  732.57      98  725.36
   156.7  702.57   215.5  681.78   313.5   645.8   352.6  629.41     382  615.55
     431  593.53   450.6  586.38     480  576.78   489.8  575.39   499.6  575.57
   519.2  577.85   529.2 578.558   626.9  581.93   636.7  583.34   675.9  594.59
   685.7  596.34   695.5  597.06   852.2  603.44   871.8  604.45   881.6  605.51
   901.2  609.58   930.6  617.45  1008.9  637.26  1018.7  639.64  1028.5  641.19
#Mann= 3 , 0 , 0
       0      .1       0   489.8    .045       0   529.2     .06       0
Bank Sta=489.8,529.2
XS Rating Curve= 0 ,0
Exp/Cntr=0.3,0.1

Type RM Length L Ch R = 1 ,4528.1  ,1452.9,1421.5,1387.1
XS GIS Cut Line= 2
     1683354.225      544544.735     1684462.997      546265.156
#Sta/Elev= 30
       0  619.92    39.4  612.13   196.8  603.98     246   618.9   314.9   634.8
     433  654.98   531.4  667.83   600.2   685.5   659.3  697.51     679  697.09
   767.5  670.45   777.4  669.44   905.3  702.63  1092.3   672.8  1161.1  653.95
  1210.3  643.28  1348.1  637.34  1387.5  633.63  1525.2  602.15    1604  580.33
  1643.3  575.41  1653.2  575.26    1712 579.413  1751.6  582.18  1790.9  592.41
  1840.1  591.09  1899.2   596.8  1938.5  606.23  2027.1  618.86  2046.8  624.39
#Mann= 3 , 0 , 0
       0      .1       0  1643.3    .045       0    1712     .06       0
Bank Sta=1643.3,1712
XS Rating Curve= 0 ,0
Exp/Cntr=0.3,0.1

Type RM Length L Ch R = 1 ,3106.6  ,519.2,541.5,544.8
XS GIS Cut Line= 2
     1682569.812      547018.144     1684360.966      546325.101
#Sta/Elev= 30
       0  678.12      49  705.16     147  738.09   186.2  746.92   215.6  756.53
     294  776.88     392  787.51   401.8  785.78   627.1   712.4   646.7  702.47
   715.3  662.92   793.7  627.14   862.3  604.54   940.7  581.42   960.3  579.32
    1215  578.98  1233.3  577.35  1254.2  571.82    1264  571.81  1283.6  574.42
  1342.4  580.51    1362  587.06  1391.4   602.6  1401.2  606.31  1440.4  616.35
  1450.2   617.3  1518.8  621.27  1675.6  622.06  1832.4  627.05  1920.6  627.84
#Mann= 3 , 0 , 0
       0     .06       0  1233.3    .045       0  1283.6      .1       0
Bank Sta=1233.3,1283.6
XS Rating Curve= 0 ,0
Exp/Cntr=0.3,0.1

Type RM Length L Ch R = 1 ,2565.2  ,618.8,620.2,621.7
XS GIS Cut Line= 2
     1683355.654      547131.206     1684272.844      546832.127
#Sta/Elev= 30
       0   677.8    29.2  664.86    48.7     657    87.7  643.11   107.2   637.4
   155.9  626.52   214.4  609.33   292.3  585.38   311.8  581.37   321.6  579.96
   389.8  577.31     419   570.9   428.8  570.66   438.5     572     458   577.5
   467.7  578.91   477.5  579.29   594.4  579.85   613.9  580.44   623.7     582
   643.2  586.73   740.6  612.06   769.8  622.93   799.1  635.51   818.6  644.82
   847.8  659.81   906.2  691.83   925.7  701.98   945.2  710.31   964.7  717.13
#Mann= 3 , 0 , 0
       0      .1       0   389.8    .045       0     458     .06       0
Bank Sta=389.8,458
XS Rating Curve= 0 ,0
Exp/Cntr=0.3,0.1

Type RM Length L Ch R = 1 ,1944.9  ,641.4,644,642.4
XS GIS Cut Line= 2
     1683681.229      547478.539     1684598.419       547179.46
#Sta/Elev= 30
       0  643.28   175.4  591.33   204.6  581.45   214.4  579.98   263.1  577.93
   409.3  577.44     419  577.04   428.8  575.55   448.2  570.87     458  570.76
   467.7  572.72   477.5   575.9   506.7  586.39     536  598.96   584.7  621.25
   594.4  624.81   604.2  626.61   643.2  628.44   652.9  631.28   682.1  647.23
   721.1  673.09   740.6  684.85   760.1  694.37   799.1  710.01   808.8  713.55
   828.3  719.13   886.8  731.69     916  738.96   935.5  745.45   964.7  757.96
#Mann= 3 , 0 , 0
       0     .06       0   428.8    .045       0   477.5     .06       0
Bank Sta=428.8,477.5
XS Rating Curve= 0 ,0
Exp/Cntr=0.3,0.1

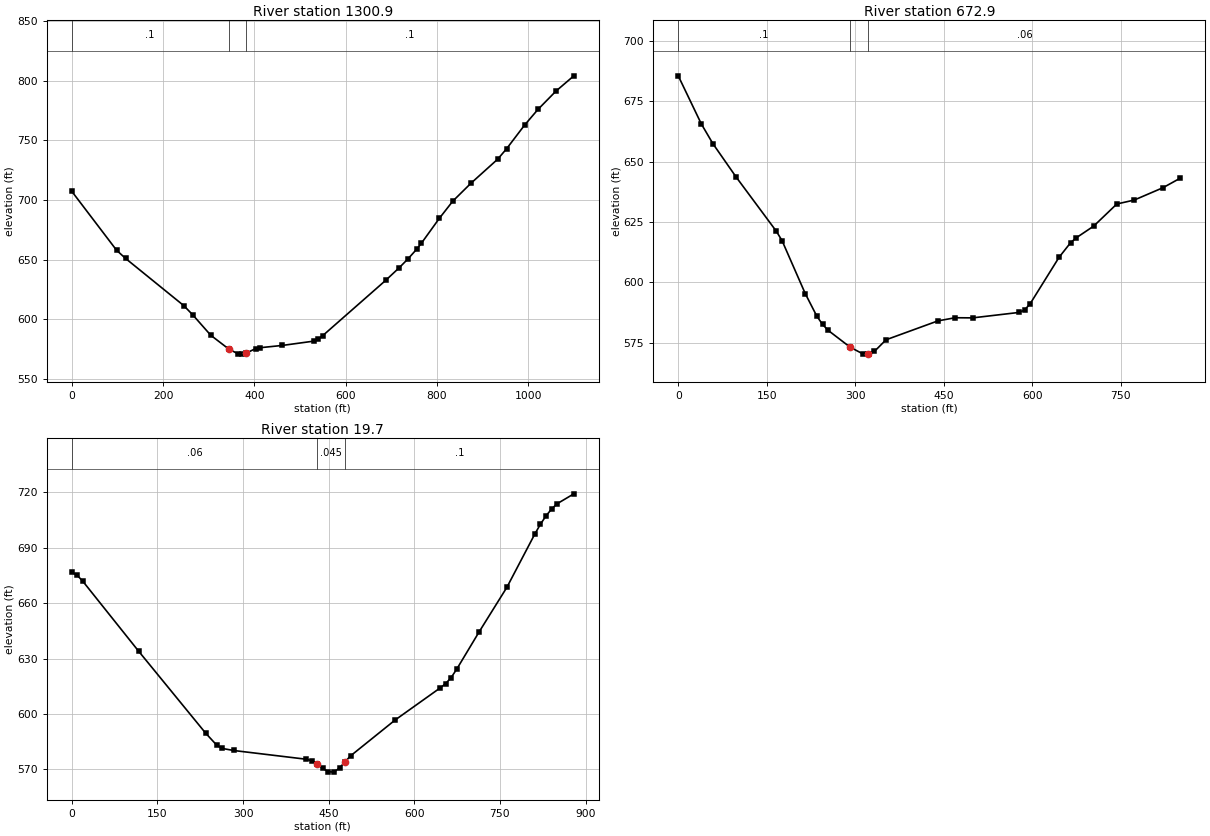
Type RM Length L Ch R = 1 ,1300.9  ,612.3,628.1,643.6
XS GIS Cut Line= 2
      1683687.82      547782.339      1684751.47       547502.64
#Sta/Elev= 30
       0  707.25    98.2  657.79   117.8  650.94   245.5  611.29   265.1  603.56
   304.4   586.5   343.7  574.96   363.3  571.06   373.2  570.64     382 571.475
   402.6  575.26   412.4  576.02   461.5  577.95   530.3  581.55   540.1  583.27
   549.9  586.21   687.4  632.46   716.8  642.95   736.5  650.56   756.1  658.92
   765.9   663.7   805.2  684.59   834.7  699.03     874  713.87   932.9  734.19
   952.5  742.97   991.8  762.76  1021.2  775.96  1060.5  791.28  1099.8  804.15
#Mann= 3 , 0 , 0
       0      .1       0   343.7    .045       0     382      .1       0
Bank Sta=343.7,382
XS Rating Curve= 0 ,0
Exp/Cntr=0.3,0.1

Type RM Length L Ch R = 1 ,672.9   ,643.9,653.2,662.4
XS GIS Cut Line= 2
     1683786.603      548073.351      1684575.56       548391.83
#Sta/Elev= 30
       0  685.59    39.1  665.67    58.7  657.49    97.8  643.76   166.2  621.21
     176  617.26   215.2  595.38   234.7  586.08   244.5  582.59   254.3  580.08
   291.4  573.14   312.9  570.38   322.3 570.284   322.7  570.28   332.5  571.42
   352.1  576.22   440.1  584.06   469.4  585.36   498.8   585.3     577  587.54
   586.8  588.52   596.6  591.25   645.4  610.42     665  616.49   674.8  618.53
   704.1  623.34   743.2  632.49   772.6  634.11   821.5  639.24   850.8   643.2
#Mann= 3 , 0 , 0
       0      .1       0   291.4    .045       0   322.3     .06       0
Bank Sta=291.4,322.3
XS Rating Curve= 0 ,0
Exp/Cntr=0.3,0.1

Type RM Length L Ch R = 1 ,19.7    ,15,19.7,24.4
XS GIS Cut Line= 2
     1683532.764      548420.958     1684158.064      549039.227
#Sta/Elev= 30
       0  676.75     9.8  675.04    19.5  671.83   117.2  633.98   234.5  589.63
     254   583.1   263.8  581.35   283.4  580.25   410.4  575.52   420.1   574.7
   429.9  573.12   439.7  570.54   449.4  568.79   459.2  568.53     469   570.8
   478.8  574.18   488.5  577.38   566.7  596.83   644.9  614.05   654.6  616.39
   664.4   619.7   674.2  624.26   713.2  644.34   762.1   668.6     811  697.45
   820.7  702.68   830.5  707.24   840.3  710.97     850  713.85   879.4  719.24
#Mann= 3 , 0 , 0
       0     .06       0   429.9    .045       0   478.8      .1       0
Bank Sta=429.9,478.8
XS Rating Curve= 0 ,0
Exp/Cntr=0.3,0.1

Chan Stop Cuts=-1
Use User Specified Reach Order=0
Composite Channel Slope=5